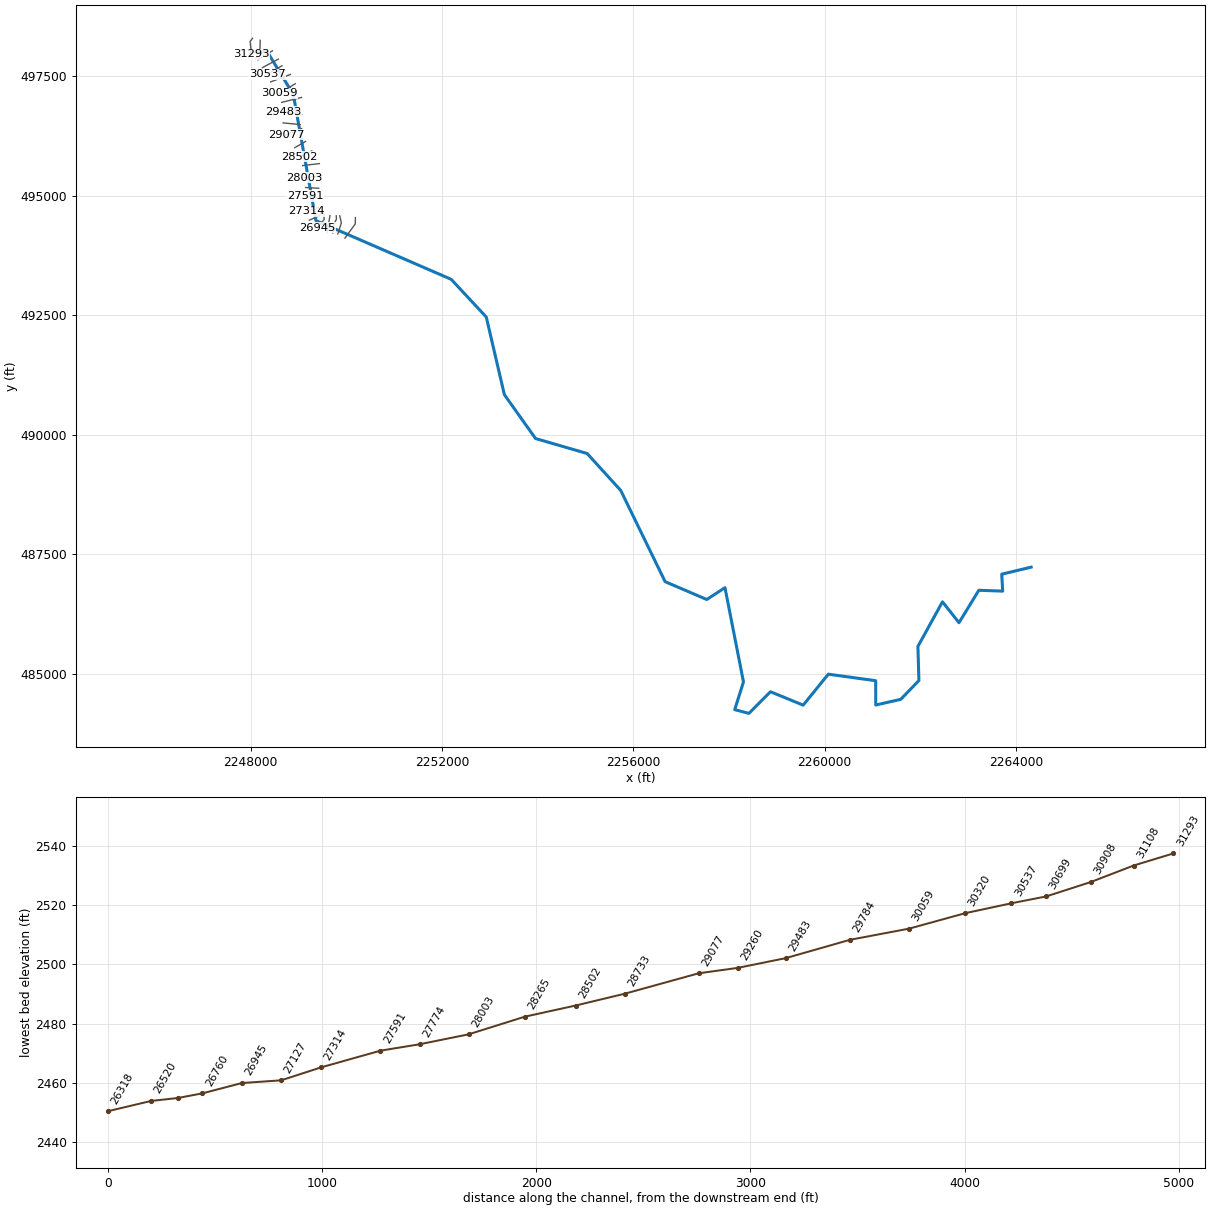
--- CLOVERCK.prj (project) ---

Proj Title=CLOVERCK
Current Plan=p01
Default Exp/Contr=0,0
English Units
Geom File=g01
Flow File=f01
Plan File=p01
Background Map Layer=Inundation Boundary (01pct Value_0)
BEGIN DESCRIPTION:
----------MODEL BY WOOD PLC 2021----------
Stream Name: Clover Creek
Flood Zone: Enhanced Approximate
Pocahontas County, WV
HEC-RAS Version: RAS 6.1
Vertical Datum: NAVD88
Projection: NAD 1983 StatePlane West Virginia S FIPS 4702 (US Feet)
Terrain: 1-meter LIDAR (FEMA Region III 3DEP collected 2016-2018)
Land Use: 2019 NLCD
Hydrologic Method:
WV SIR2010-5033 regression equations
Hydraulics - Normal depth Tie in with Clover Creek
END DESCRIPTION:
DSS Export Rating Curves= 0
DSS Export Rating Curve Sorted= 0
DSS Export Volume Flow Curves= 0
DXF OffsetX= 0
DXF OffsetY= 0
DXF ScaleX= 0
DXF ScaleY= 0

--- CLOVERCK.p01 (plan) ---

Plan Title=Floodplain
Program Version=6.10
Short Identifier=Floodplain
Geom File=g01
Flow File=f01
Subcritical Flow
K Sum by GR= 0
Std Step Tol= 0.01
Critical Tol= 0.01
Num of Std Step Trials= 20
Max Error Tol= 0.3
Flow Tol Ratio= 0.001
Split Flow NTrial= 30
Split Flow Tol= 0.02
Split Flow Ratio= 0.02
Log Output Level= 0
Friction Slope Method= 1
Unsteady Friction Slope Method= 2
Unsteady Bridges Friction Slope Method= 1
Parabolic Critical Depth
Global Vel Dist= 0 , 0 , 0
Global Log Level= 0
CheckData=True
Encroach Param=-1 ,0,0, 0
Mapping Interval=1HOUR
Computation Time Step Use Courant=        0
Computation Time Step Use Time Series=    0
Computation Time Step Count To Double=0
Computation Time Step Max Doubling=0
Computation Time Step Max Halving=0
Computation Time Step Residence Courant=0
Run HTab= 0
Run UNet= 0
Run Sediment= 0
Run PostProcess= 0
Run WQNet= 0
Run RASMapper=-1
UNET Theta= 0
UNET Theta Warmup= 0
UNET ZTol= 0
UNET ZSATol= 0
UNET MxIter= 0
UNET Max Iter WO Improvement= 0
UNET MaxInSteps= 0
UNET DtIC= 0
UNET DtMin= 0
UNET MaxCRTS= 0
UNET WFStab= 0
UNET SFStab= 0
UNET WFX= 1
UNET SFX= 1
UNET Gravity=32.174
UNET 1D Methodology=Finite Difference
UNET DSS MLevel= 1
UNET Pardiso=0
UNET DZMax Abort= 0
UNET Use Existing IB Tables= 0
UNET Froude Reduction=False
UNET Froude Limit= 0
UNET Froude Power= 0
UNET D1 Cores= 0
UNET WindReference=Eulerian
UNET WindDragFormulation=Hsu (1988)
UNET D2 Coriolis=0
UNET D2 Cores= 0
UNET D2 Theta= 1
UNET D2 Theta Warmup= 1
UNET D2 Z Tol= 0.01
UNET D2 Volume Tol= 0.01
UNET D2 Max Iterations= 20
UNET D2 Equation= 0
UNET D2 RampUpFraction=0.1
UNET D2 TimeSlices= 1
UNET D2 Turbulence Formulation=Non-Conservative (original)
UNET D2 Eddy Viscosity=0.3
UNET D2 Transverse Eddy Viscosity=0.1
UNET D2 Smagorinsky Mixing=0
UNET D2 BCVolumeCheck=0
UNET D2 Cores=0
UNET D2 SolverType=PARDISO (Direct)
UNET D2 Minimum Iterations= 2147483647
UNET D2 Maximum Iterations= 2147483647
UNET D2 Restart Number= 10
UNET D2 Relaxation Coeff=1.3
UNET D2 SOR Precondition Iterations= 10
UNET D2 ILUT Maximum Fill= 8
UNET D2 ILUT Tolerance=1E-08
UNET D1D2 MaxIter= 0
UNET D1D2 ZTol=0.01
UNET D1D2 QTol=0.1
UNET D1D2 MinQTol=1
Write IC File= 0
Write IC File at Fixed DateTime=0
Write IC File at Sim End=0
Echo Input=False
Echo Parameters=False
Echo Output=False
Write Detailed= 0
HDF Write Warmup=0
HDF Write Time Slices=0
HDF Flush=0
HDF Compression= 1
HDF Chunk Size= 1
HDF Spatial Parts= 1
HDF Use Max Rows=0
HDF Fixed Rows= 1
Calibration Method= 0
Calibration Iterations= 20
Calibration Max Change=0.05
Calibration Tolerance=0.2
Calibration Maximum=1.5
Calibration Minimum=0.5
Calibration Optimization Method= 1
WQ AD Non Conservative
WQ ULTIMATE=-1
WQ Max Comp Step=1HOUR
WQ Output Interval=15MIN
WQ Output Selected Increments= 0
WQ Output face flow=0
WQ Output face velocity=0
WQ Output face area=0
WQ Output face dispersion=0
WQ Output cell volume=0
WQ Output cell surface area=0
WQ Output cell continuity=0
WQ Output cumulative cell continuity=0
WQ Output face conc=0
WQ Output face dconc_dx=0
WQ Output face courant=0
WQ Output face peclet=0
WQ Output face adv mass=0
WQ Output face disp mass=0
WQ Output cell mass=0
WQ Output cell source sink temp=0
WQ Output nsm pathways=0
WQ Output nsm derived pathways=0
WQ Create Restart=0
WQ Fixed Restart=0
WQ System Summary=0
WQ Write To DSS=0
Sorting and Armoring Iterations= 10
XS Update Threshold= 0.02
Bed Roughness Predictor= 0
Hydraulics Update Threshold= 0.02
Energy Slope Method= 1
Volume Change Method= 1
Sediment Retention Method= 0
Sediment TS Multiplier= 1
Warm Up Method= 0
XS Weighting Method= 0
Number of US Weighted Cross Sections= 1
Number of DS Weighted Cross Sections= 1
Upstream XS Weight=0
Main XS Weight=1
Downstream XS Weight=0
Number of DS XS's Weighted with US Boundary= 1
Upstream Boundary Weight= 1
Weight of XSs Associated with US Boundary= 0
Number of US XS's Weighted with DS Boundary= 1
Downstream Boundary Weight= 0.5
Weight of XSs Associated with DS Boundary= 0.5
Percentile Method= 0
Sediment Output Level= 3
Mass or Volume Output= 0
Output Increment Type= 1
Profile and TS Output Increment= 1
Transport Output Increment 1
XS Output Flag= 0
XS Output Increment= 10
Read HDF5 Sediment Hotstart= 0
Sediment Hotstart Type= 0
Write Gradation File= 0
Read Gradation Hotstart= 0
Write HDF5 File= 1
Write Binary Output= 1
Write DSS Sediment File= 0
DSS Sediment Output Type= 1
SV Curve= 0
Specific Gage Flag= 0
Subcell Erosion Methods= 0
Subcell Deposition Methods= 0
Advection Scheme= 1
Matrix Solver= 0
Implicit Weighting Factor= 1
Maximum Outer Loop Convergence Iterations= 5
Convergence Maximum Absolute= 0.001
Convergence RMSE= 0.0001
Grain Fractions Max Abs Error= 0.001
Max Subgrid Regions= 1
Max Subgrid Length Scale= 3.402823E+38
Initial Layer Thickness= 3.402823E+38
Min Layer Thickness= 3.402823E+38
Max Layer Thickness= 3.402823E+38
Number of Layers= 5

--- CLOVERCK.f01 (steady flow) ---

Flow Title=Flow
Program Version=6.10
Number of Profiles= 6
Profile Names=01pct,10pct,04pct,02pct,0_2pct,01plus
River Rch & RM=CLOVERCK,Main            ,31293
    2030    1130    1460    1740    2770    3000
River Rch & RM=CLOVERCK,Main            ,22810
    2290    1270    1650    1960    3110    3380
River Rch & RM=CLOVERCK,Main            ,18656
    2580    1440    1870    2210    3500    3810
River Rch & RM=CLOVERCK,Main            ,11630
    3020    1700    2190    2590    4090    4470
River Rch & RM=CLOVERCK,Main            ,613
    3360    1900    2450    2890    4540    4970
Boundary for River Rch & Prof#=CLOVERCK,Main            , 1
Up Type= 0
Dn Type= 3
Dn Slope=0.00382
Boundary for River Rch & Prof#=CLOVERCK,Main            , 2
Up Type= 0
Dn Type= 3
Dn Slope=0.00382
Boundary for River Rch & Prof#=CLOVERCK,Main            , 3
Up Type= 0
Dn Type= 3
Dn Slope=0.00382
Boundary for River Rch & Prof#=CLOVERCK,Main            , 4
Up Type= 0
Dn Type= 3
Dn Slope=0.00382
Boundary for River Rch & Prof#=CLOVERCK,Main            , 5
Up Type= 0
Dn Type= 3
Dn Slope=0.00382
Boundary for River Rch & Prof#=CLOVERCK,Main            , 6
Up Type= 0
Dn Type= 3
Dn Slope=0.00382
DSS Import GetInterval= 0
DSS Import GetPeak= 0
DSS Import FillOption= 0

--- CLOVERCK.g01 (geometry) ---

Geom Title=Geometry
Program Version=6.10

River Reach=CLOVERCK        ,Main
Reach XY= 30
     2248003.044      498005.583     2248344.785      498019.855
     2248891.375      497121.663      2249364.32      494481.875
     2252192.371      493254.562     2252925.774      492465.138
      2253303.82      490842.275     2253955.621       489924.07
     2255034.351      489610.933     2255736.926      488837.595
     2256664.391      486930.251     2257534.556      486556.824
     2257915.731       486804.63     2258302.221      484833.948
     2258119.605      484252.879     2258416.091      484174.836
      2258866.47      484627.778     2259550.415       484346.97
     2260076.268      484994.713     2261066.686      484858.099
     2261067.482      484349.586     2261590.099      484468.372
      2261969.92      484861.841     2261949.256       485575.83
     2262462.682      486508.656     2262807.834      486071.265
     2263222.944      486750.037     2263721.746      486732.243
     2263701.497      487086.332      2264316.49      487233.902

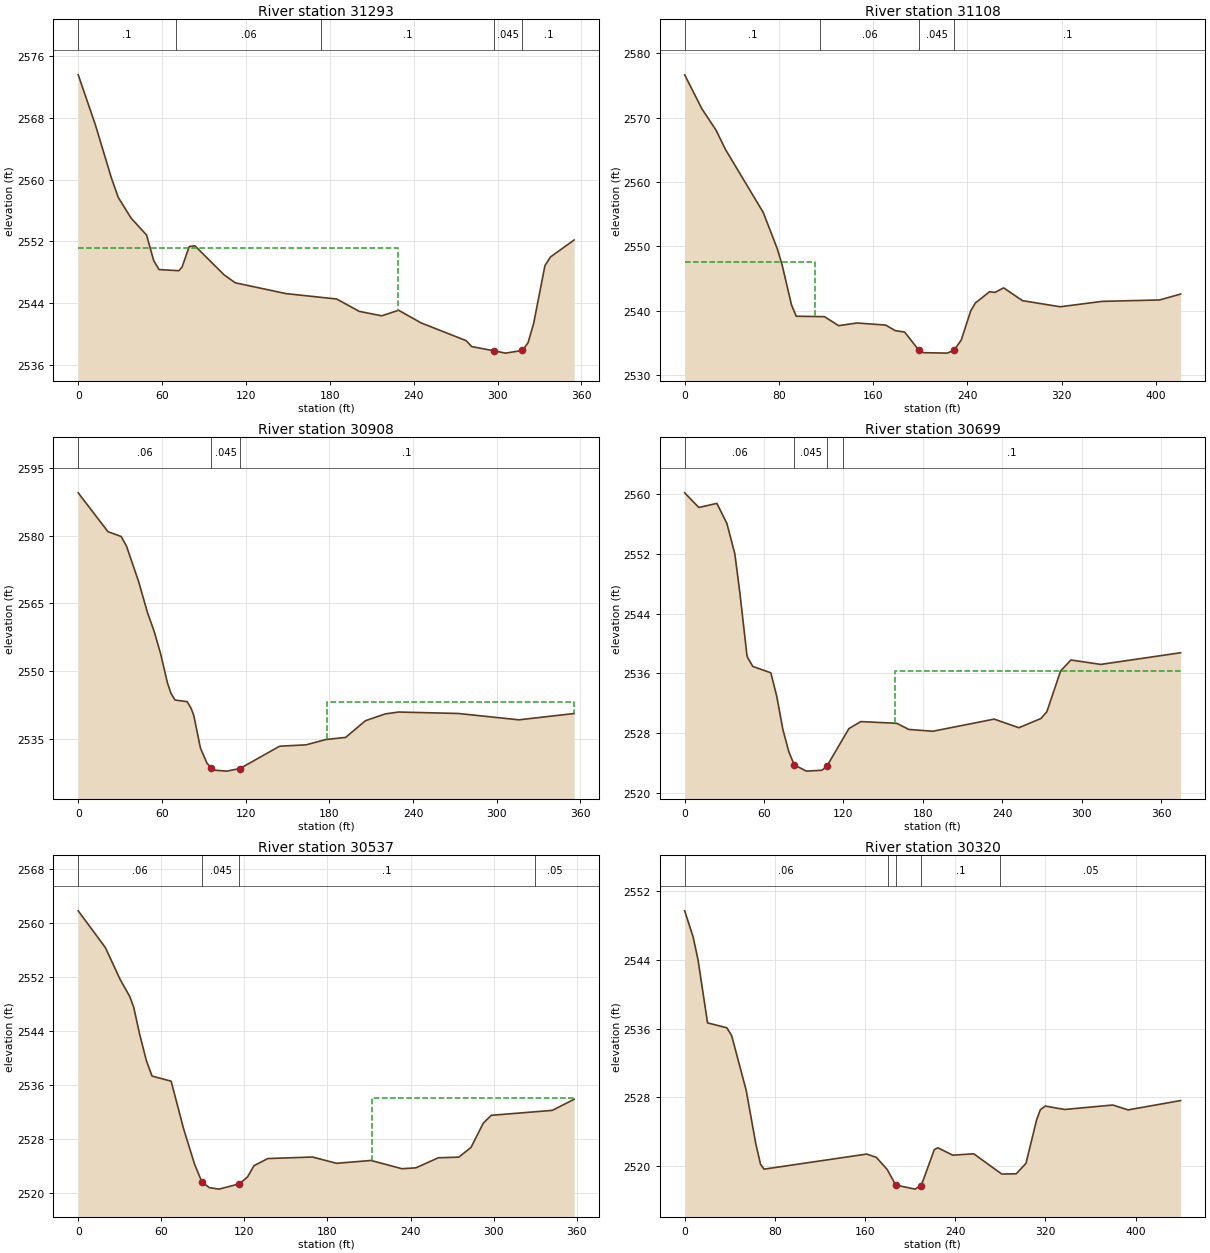
Type RM Length L Ch R = 1 ,31293   ,190.3,185.7,182.6
XS GIS Cut Line= 3
2248038.73720102498295.7163868182247987.33798865498229.909045338
2248018.50450907497960.446375334
#Sta/Elev= 30
       0 2573.58    12.2 2567.14    23.6 2560.29    28.6 2557.69    37.8    2555
    48.9  2552.8      54 2549.49    57.8 2548.32      72 2548.17    74.3 2548.64
    79.4 2551.31    83.5  2551.4   104.4 2547.63   112.4  2546.6   148.7  2545.2
   184.9  2544.5     201  2542.9   217.1 2542.32   229.2 2543.04   245.3  2541.4
   277.5  2539.1   281.5 2538.33   297.4 2537.78   305.7 2537.48   317.8 2537.83
   321.8 2538.82   325.8 2541.31   333.9 2548.83   337.9 2549.96   354.8 2552.16
#Mann= 5 ,-1,0
       0      .1       0      70     .06       0   173.5      .1       0
   297.4    .045       0   317.8      .1       0
#XS Ineff= 2 , 0
          228.51 2551.18
Permanent Ineff=
       F       F
Bank Sta=297.4,317.8
XS Rating Curve= 0 ,0
Exp/Cntr(USF)=0,0
Exp/Cntr=0.3,0.1

Type RM Length L Ch R = 1 ,31108   ,219,200.2,177
XS GIS Cut Line= 4
2248198.93325601498255.8391563562248198.26281818498180.750118539
2248189.54712629 497934.699432122248105.07195874497881.734842945
#Sta/Elev= 30
       0 2576.68    14.7 2571.37    26.7 2568.05    34.7 2565.05    66.7 2555.27
    78.7 2549.58    82.7 2547.12    90.7 2540.88    94.7 2539.13   118.7 2539.06
   130.7 2537.66   146.3 2538.08   170.7 2537.75   178.7 2536.89   186.7 2536.67
   198.7 2533.87   202.7 2533.46   222.8 2533.39  228.78 2533.86   234.8 2535.44
   242.8 2539.96   246.8 2541.19   258.8 2542.94   263.4 2542.84   270.8 2543.54
   286.8 2541.55   318.8  2540.6   354.3 2541.44   403.2 2541.66     421 2542.58
#Mann= 4 ,-1,0
       0      .1       0  115.09     .06       0   198.7    .045       0
  228.78      .1       0
#XS Ineff= 2 , 0
          110.47 2547.56
Permanent Ineff=
       F       F
Bank Sta=198.7,228.78
XS Rating Curve= 0 ,0
Exp/Cntr(USF)=0,0
Exp/Cntr=0.3,0.1

Type RM Length L Ch R = 1 ,30908   ,210.8,208.5,206.8
XS GIS Cut Line= 2
  2248454.218221498034.9099254982248153.75681634497844.938598067
#Sta/Elev= 30
       0 2589.55    21.3 2580.94    30.8 2579.86    34.6 2577.74    43.3 2569.87
    49.7 2562.93    54.5 2558.76    59.2  2553.7    63.9 2547.46    66.5 2545.06
    69.4 2543.59    78.1 2543.22      81 2541.69    82.9  2540.1    87.6 2532.95
    92.3 2529.57    95.5 2528.51    98.4    2528   106.5 2527.81     116 2528.39
   144.4 2533.34   163.3 2533.64   177.5 2534.82   191.7 2535.29   205.9    2539
   220.2 2540.51   229.6 2540.92   272.4  2540.6   315.9 2539.19   355.5 2540.59
#Mann= 3 ,-1,0
       0     .06       0    95.5    .045       0     116      .1       0
#XS Ineff= 2 , 0
                          178.07         2543.05
Permanent Ineff=
       F       F
Bank Sta=95.5,116
XS Rating Curve= 0 ,0
Exp/Cntr(USF)=0,0
Exp/Cntr=0.3,0.1

Type RM Length L Ch R = 1 ,30699   ,161.3,161.8,162.6
XS GIS Cut Line= 2
 2248577.5995545497860.2246352642248247.07422156497683.608045141
#Sta/Elev= 30
       0 2560.13    10.7 2558.17    24.3 2558.72    31.9 2556.04    37.9 2551.98
    41.7 2546.78      47 2538.51    47.6 2538.11    51.5 2536.93    65.1 2536.08
    69.6 2532.93    74.2 2528.52    78.7 2525.53    82.8 2523.77      92 2522.94
   103.8 2523.06  107.642523.653   124.1 2528.62   133.1 2529.56   160.3 2529.33
   169.4 2528.51   187.6 2528.27   233.9 2529.89   252.6 2528.74   269.2 2529.97
   273.7 2530.87   284.1 2536.33   291.9 2537.79   314.5  2537.2   374.8 2538.76
#Mann= 4 ,-1,0
       0     .06       0    82.8    .045       0  107.64     .06       0
     120      .1       0
#XS Ineff= 2 , 0
                          159.29         2536.28
Permanent Ineff=
       F       F
Bank Sta=82.8,107.64
XS Rating Curve= 0 ,0
Exp/Cntr(USF)=0,0
Exp/Cntr=0.3,0.1

Type RM Length L Ch R = 1 ,30537   ,219.9,216.8,212.7
XS GIS Cut Line= 2
2248654.55392591 497721.454457312248342.95179905497544.837867187
#Sta/Elev= 30
       0 2561.81    19.6 2556.38    30.3 2551.65    37.2 2549.15    40.1 2547.55
    44.1 2543.79    49.2 2539.67    53.3 2537.37    67.1 2536.61    76.3 2529.44
    84.1 2524.29    89.42521.681    94.7 2520.86   101.7 2520.64   116.4 2521.42
   122.3 2522.44   126.9  2524.1   136.9 2525.16   169.2 2525.39   186.6 2524.46
   211.5 2524.88   233.8 2523.66   243.9 2523.79   260.1 2525.28   274.9 2525.37
   283.7 2526.81   292.5 2530.37   298.3 2531.56   342.4 2532.29   358.2 2533.93
#Mann= 4 ,-1,0
       0     .06       0    89.4    .045       0   116.4      .1       0
     330     .05       0
#XS Ineff= 2 , 0
                          212.06         2534.13
Permanent Ineff=
       F       F
Bank Sta=89.4,116.4
XS Rating Curve= 0 ,0
Exp/Cntr(USF)=0,0
Exp/Cntr=0.3,0.1

Type RM Length L Ch R = 1 ,30320   ,257.9,261.4,265.6
XS GIS Cut Line= 2
2248831.17051604 497541.053225972248419.90617046497384.621389004
#Sta/Elev= 30
       0 2549.73     7.5 2546.68    11.8 2544.05    20.3 2536.66    37.4 2536.09
    41.7 2535.17    54.6 2528.78    63.1 2522.56    67.3 2520.17    70.4  2519.6
   161.5 2521.36   170.1 2520.97   179.7 2519.56   187.2 2517.75   204.3 2517.27
   209.9 2517.69   221.5 2521.88   224.7 2522.09   237.8 2521.23   256.5 2521.39
   281.3 2519.03   294.2 2519.06   302.8 2520.28   312.3 2525.38   315.6 2526.54
   319.9 2526.96   337.1 2526.56   379.8 2527.08   393.4 2526.51     440  2527.6
#Mann= 5 ,-1,0
       0     .06       0     180      .1       0   187.2    .045       0
   209.9      .1       0     280     .05       0
Bank Sta=187.2,209.9
XS Rating Curve= 0 ,0
Exp/Cntr(USF)=0,0
Exp/Cntr=0.3,0.1

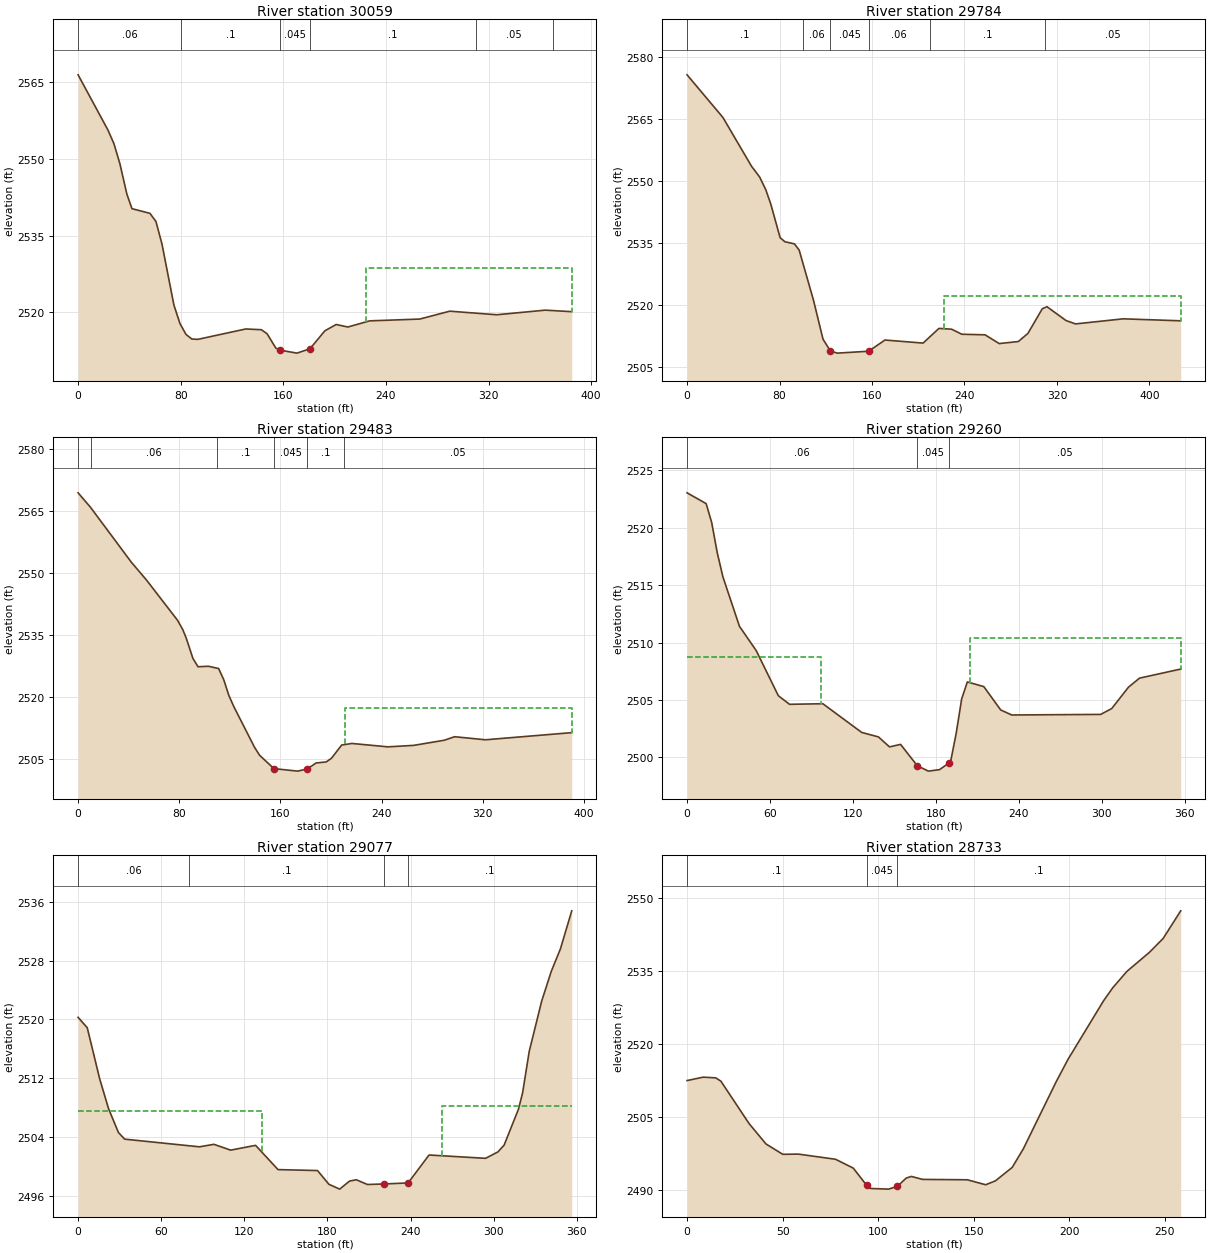
Type RM Length L Ch R = 1 ,30059   ,284.7,274.7,268.8
XS GIS Cut Line= 2
2248932.09428182497345.5134297622248602.83049595497146.188992338
#Sta/Elev= 30
       0 2566.39    23.3  2555.6      28 2552.91    32.6 2549.03      38 2543.13
      42 2540.26      56 2539.35    60.7 2537.76    65.4 2533.36    74.7 2521.45
    79.4 2517.85    84.1 2515.72    88.7 2514.81    93.4 2514.75   130.8 2516.78
   142.9 2516.63   147.4 2515.83   154.2 2513.03   157.72512.633   170.6 2512.06
   180.8 2512.91   192.4 2516.42   201.2 2517.65   210.3 2517.16   227.4 2518.36
   266.4 2518.71   289.8 2520.25   326.4 2519.55   364.3 2520.45   384.9 2520.15
#Mann= 6 ,-1,0
       0     .06       0      80      .1       0   157.7    .045       0
   180.8      .1       0     310     .05       0     370      .1       0
#XS Ineff= 2 , 0
                          224.43         2528.62
Permanent Ineff=
       F       F
Bank Sta=157.7,180.8
XS Rating Curve= 0 ,0
Exp/Cntr(USF)=0,0
Exp/Cntr=0.3,0.1

Type RM Length L Ch R = 1 ,29784   ,314.4,301.7,293.1
XS GIS Cut Line= 2
2249062.29952115497059.1711261562248647.88130789496955.850420934
#Sta/Elev= 30
       0 2575.66      31 2565.35    55.8 2553.52    62.8 2550.93    68.1 2547.86
    72.3 2544.51    80.5 2536.26    84.6 2535.27    92.9 2534.75      97 2533.24
   109.4 2521.09   117.6 2511.69     124 2508.83     130 2508.31   157.1 2508.77
   171.2 2511.48   204.2 2510.74   217.9 2514.29   228.9  2514.1   237.7 2512.88
   257.8 2512.74   270.1 2510.62   286.6 2511.12   294.9 2513.08   307.3 2519.04
   311.4 2519.54   327.9 2516.19   336.1 2515.38   377.3 2516.61   427.1 2516.13
#Mann= 6 ,-1,0
       0      .1       0     100     .06       0     124    .045       0
   157.1     .06       0     210      .1       0     310     .05       0
#XS Ineff= 2 , 0
                          222.59         2522.24
Permanent Ineff=
       F       F
Bank Sta=124,157.1
XS Rating Curve= 0 ,0
Exp/Cntr(USF)=0,0
Exp/Cntr=0.3,0.1

Type RM Length L Ch R = 1 ,29483   ,221.5,223,224.4
XS GIS Cut Line= 2
2249065.70569824496700.3871387912248680.80768648496765.104503601
#Sta/Elev= 30
       0 2569.48     9.7 2566.02    42.1 2552.68    54.1 2548.35    78.6 2538.63
    82.7  2536.4    85.4 2534.38    90.8 2529.37    94.8 2527.37     103 2527.48
   111.1 2526.94   115.1 2524.28   119.2 2520.41   123.2 2517.66   139.5 2507.86
   143.5 2505.93  154.862502.695   173.6 2502.09   181.3 2502.63   188.1 2504.06
   196.2 2504.32   200.3  2505.2   208.4 2508.41   216.5 2508.79   244.9 2507.97
   265.2 2508.32   289.5 2509.57   297.7 2510.42     322 2509.68   390.3 2511.41
#Mann= 6 ,-1,0
       0      .1       0      10     .06       0     110      .1       0
  154.86    .045       0   181.3      .1       0     210     .05       0
#XS Ineff= 2 , 0
                          211.32         2517.38
Permanent Ineff=
       F       F
Bank Sta=154.86,181.3
XS Rating Curve= 0 ,0
Exp/Cntr(USF)=0,0
Exp/Cntr=0.3,0.1

Type RM Length L Ch R = 1 ,29260   ,179.9,182.7,185.5
XS GIS Cut Line= 2
2249033.91471202496492.6103359822248678.53690175496526.672106934
#Sta/Elev= 30
       0 2523.05    13.8 2522.11    17.8 2520.47    21.8 2517.85    25.9 2515.74
    37.9 2511.42      50 2509.31      66 2505.38    74.1 2504.63    98.2 2504.68
   126.3 2502.18   138.4 2501.79   146.4 2500.92   154.4 2501.14   166.5 2499.28
   174.5 2498.81   182.6 2498.94   189.42499.522   190.6 2499.65   194.6 2502.09
   198.6 2505.11   202.7 2506.58   214.6 2506.17   226.8 2504.14   234.8  2503.7
   299.1 2503.75   307.1 2504.26   319.2 2506.12   327.2 2506.91     357  2507.7
#Mann= 3 ,-1,0
       0     .06       0   166.5    .045       0   189.4     .05       0
#XS Ineff= 2 , 0
           96.92 2508.72  204.65         2510.44
Permanent Ineff=
       F       F
Bank Sta=166.5,189.4
XS Rating Curve= 0 ,0
Exp/Cntr(USF)=0,0
Exp/Cntr=0.3,0.1

Type RM Length L Ch R = 1 ,29077   ,334.1,344.1,352.4
XS GIS Cut Line= 4
2249066.05818727496407.2550842762248914.90364188496329.391829084
2248835.77029367496326.1618965042248740.95890202496276.426606658
#Sta/Elev= 30
       0 2520.29     6.6 2518.88    15.6 2511.93      22 2507.89    29.1 2504.67
    33.6 2503.76    87.6 2502.72      98 2503.06   110.1 2502.27   128.1 2502.92
   144.3 2499.63   172.8  2499.5     181 2497.64   188.8 2496.98   195.9 2498.07
   200.8 2498.25   208.8 2497.61   220.8 2497.68   238.2 2497.82   253.3 2501.61
   294.1 2501.16     303 2502.03   307.5 2502.96   317.8 2507.81   320.8 2510.02
   325.6 2515.67   334.6  2522.5   341.5 2526.52   348.1 2529.57   356.3 2534.74
#Mann= 4 ,-1,0
       0     .06       0      80      .1       0   220.8    .045       0
   238.2      .1       0
#XS Ineff= 2 , 0
          132.89 2507.59  262.96         2508.26
Permanent Ineff=
       F       F
Bank Sta=220.8,238.2
XS Rating Curve= 0 ,0
Exp/Cntr(USF)=0,0
Exp/Cntr=0.3,0.1

Type RM Length L Ch R = 1 ,28733   ,231.2,230.3,228.8
XS GIS Cut Line= 2
2249147.45394853496138.3679180782248923.78165261496008.933188459
#Sta/Elev= 30
       0 2512.42     8.4 2513.12      15 2512.98    17.7  2512.3    32.5 2503.56
    41.3 2499.39    50.1 2497.26    58.3  2497.3    77.7 2496.24      87 2494.42
      94 2490.88    96.2 2490.23   105.5  2490.1   110.1 2490.68   114.7 2492.37
   117.4 2492.71   123.3  2492.1   146.7 2492.02   156.3    2491   161.4  2491.8
   170.2 2494.57     176 2498.38   193.3 2512.25   199.4 2516.78     218 2528.82
   222.8 2531.49   230.2 2534.86     242 2538.78   249.2 2541.64   258.4 2547.32
#Mann= 3 ,-1,0
       0      .1       0      94    .045       0   110.1      .1       0
Bank Sta=94,110.1
XS Rating Curve= 0 ,0
Exp/Cntr(USF)=0,0
Exp/Cntr=0.3,0.1

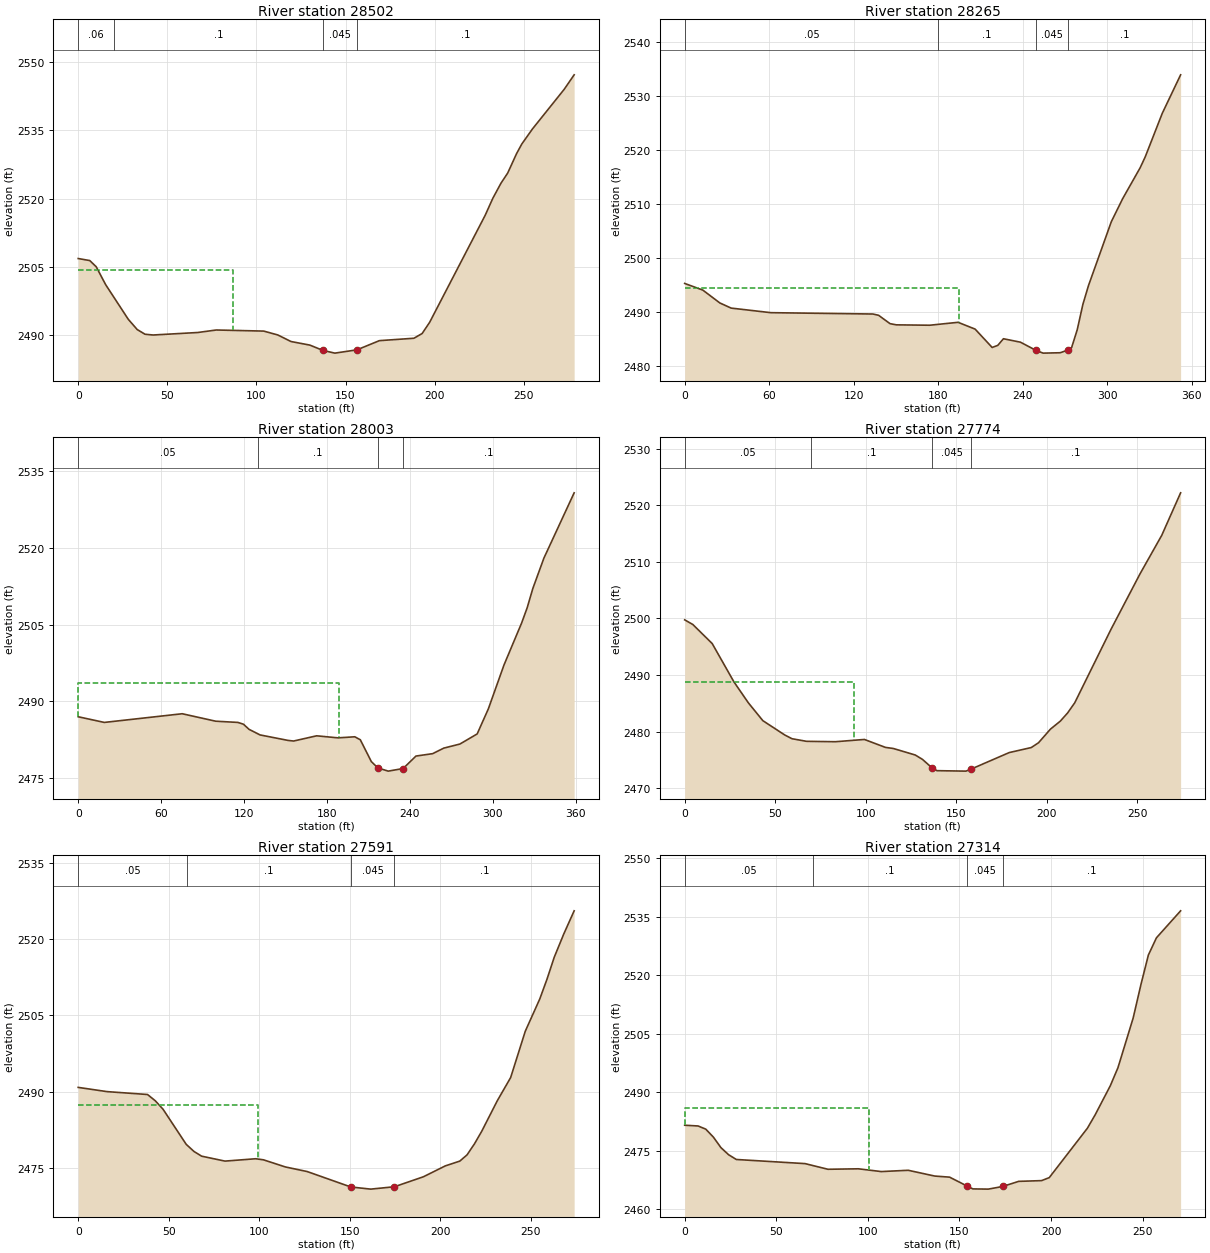
Type RM Length L Ch R = 1 ,28502   ,243,237.4,230.1
XS GIS Cut Line= 2
2249278.02407051495940.8096465542249027.10235783495820.458055856
#Sta/Elev= 30
       0 2506.87     6.5 2506.42    10.1 2505.06    15.4 2501.13    28.1 2493.52
    33.1 2491.27    37.5 2490.24      42 2490.07    67.1 2490.62    77.5 2491.17
   104.1 2490.93     112 2490.08   119.4 2488.64     130 2487.85   137.42486.684
     144 2486.09   156.4 2486.81     169 2488.83   188.4 2489.36     193  2490.4
   197.2 2492.85   228.3 2516.31   232.7 2520.13   237.2 2523.39     241 2525.64
     246 2529.92   248.9 2532.01   254.9 2535.33   272.7 2544.03   278.3 2547.22
#Mann= 4 ,-1,0
       0     .06       0      20      .1       0   137.4    .045       0
   156.4      .1       0
#XS Ineff= 2 , 0
           86.71 2504.24
Permanent Ineff=
       F       F
Bank Sta=137.4,156.4
XS Rating Curve= 0 ,0
Exp/Cntr(USF)=0,0
Exp/Cntr=0.3,0.1

Type RM Length L Ch R = 1 ,28265   ,261.8,262.4,262.9
XS GIS Cut Line= 2
2249436.97900162495675.1278331262249087.27815318495634.253707983
#Sta/Elev= 30
       0 2495.26    12.9 2494.02      25 2491.63      33 2490.68    61.2 2489.83
   133.7 2489.58   137.7 2489.34   145.8 2487.79   150.3 2487.57     174  2487.5
   194.1 2488.04   206.2 2486.78   218.3 2483.37   222.3 2483.76   226.3 2484.99
   238.4 2484.35   249.5 2482.82   254.5 2482.32   266.6 2482.39   272.3 2482.91
   274.7 2483.34   278.7 2486.66   282.7 2491.36   286.7 2494.87   302.9 2506.72
   310.9 2510.97   323.4 2516.75     327 2518.77   339.1 2526.86   352.1 2533.99
#Mann= 4 ,-1,0
       0     .05       0     180      .1       0   249.5    .045       0
   272.3      .1       0
#XS Ineff= 2 , 0
          194.64 2494.47
Permanent Ineff=
       F       F
Bank Sta=249.5,272.3
XS Rating Curve= 0 ,0
Exp/Cntr(USF)=0,0
Exp/Cntr=0.3,0.1

Type RM Length L Ch R = 1 ,28003   ,232.6,229,225.5
XS GIS Cut Line= 2
2249478.98851913495421.935335713 2249122.4753165495379.925818206
#Sta/Elev= 30
       0    2487    18.9 2485.89    75.3 2487.59    99.5 2486.13   115.6 2485.89
   119.6 2485.54   123.7 2484.53   131.7 2483.44   151.9 2482.37   155.9 2482.25
   172.6 2483.27   188.1 2482.87   200.2 2483.08   204.2  2482.5   212.2 2478.22
   216.9 2476.99   224.4 2476.36   235.2 2476.87   244.5 2479.31   256.6 2479.78
   264.6 2480.86   276.3 2481.66   288.8 2483.64   296.9 2488.55   308.2 2497.12
     321 2505.36     325 2508.33   329.1 2512.11   337.1 2518.04     359 2530.82
#Mann= 4 ,-1,0
       0     .05       0     130      .1       0   216.9    .045       0
   235.2      .1       0
#XS Ineff= 2 , 0
           188.7 2493.56
Permanent Ineff=
       F       F
Bank Sta=216.9,235.2
XS Rating Curve= 0 ,0
Exp/Cntr(USF)=0,0
Exp/Cntr=0.3,0.1

Type RM Length L Ch R = 1 ,27774   ,183.9,183.1,182.5
XS GIS Cut Line= 2
2249423.35429324 495159.659699382249149.72473326495174.419800126
#Sta/Elev= 30
       0 2499.75     4.5 2498.93    15.2 2495.56    27.2 2488.79    35.2 2485.07
    43.2 2481.92    55.3 2479.39    59.3 2478.73    67.3 2478.27    83.3  2478.2
    99.3  2478.6   110.9  2477.2   115.3    2477   127.4 2475.85   131.4 2475.07
   136.52473.624   139.4 2473.08   155.4    2473   158.4 2473.38   179.3 2476.28
   191.5 2477.17   195.5 2478.02   202.1 2480.43   207.5 2481.83   211.5 2483.26
   215.5 2485.08   235.5 2498.05   251.5 2507.84   263.6 2514.71     274 2522.21
#Mann= 4 ,-1,0
       0     .05       0      70      .1       0   136.5    .045       0
   158.4      .1       0
#XS Ineff= 2 , 0
           93.69 2488.73
Permanent Ineff=
       F       F
Bank Sta=136.5,158.4
XS Rating Curve= 0 ,0
Exp/Cntr(USF)=0,0
Exp/Cntr=0.3,0.1

Type RM Length L Ch R = 1 ,27591   ,270.6,276.4,285.8
XS GIS Cut Line= 3
2249408.09003876  494944.59515432249311.29257638494980.834055639
2249141.27283297494996.421554444
#Sta/Elev= 30
       0 2490.83    15.9    2490    38.3 2489.43    42.6  2488.2    46.9 2486.53
    59.7 2479.63      64 2478.23    68.2 2477.31    81.1 2476.34    98.1  2476.8
   102.4 2476.59   114.5 2475.19   126.6 2474.28   150.7 2471.25   161.7 2470.83
   174.8  2471.3   190.8 2473.26   202.9  2475.4   210.9 2476.34   214.9 2477.56
     219 2479.73     223 2482.19   231.6 2488.19     239 2492.76   247.1 2501.88
   255.1 2508.21   259.1 2512.11   263.1 2516.42   268.4 2521.02   274.1 2525.54
#Mann= 4 ,-1,0
       0     .05       0      60      .1       0   150.7    .045       0
   174.8      .1       0
#XS Ineff= 2 , 0
            99.5 2487.45
Permanent Ineff=
       F       F
Bank Sta=150.7,174.8
XS Rating Curve= 0 ,0
Exp/Cntr(USF)=0,0
Exp/Cntr=0.3,0.1

Type RM Length L Ch R = 1 ,27314   ,184.7,187,189.9
XS GIS Cut Line= 2
2249419.22137581494757.3975622052249159.34267892494681.704737867
#Sta/Elev= 30
       0 2481.58     7.3 2481.39    11.5 2480.58    15.7 2478.52    19.8 2475.83
      24 2474.01    28.2  2472.8    65.7 2471.74    78.2 2470.29    94.8 2470.41
   107.3  2469.7     122 2470.03   136.5 2468.55   144.6 2468.27   153.92466.052
   157.3 2465.26   165.7  2465.2   173.6 2465.88   182.3 2467.19   194.8 2467.38
     199 2468.15   219.8  2480.8     224  2484.2   232.3 2491.68   236.5 2496.33
   244.8 2509.06     249 2517.56   253.1  2525.2   257.5 2529.62   270.7 2536.54
#Mann= 4 ,-1,0
       0     .05       0      70      .1       0   153.9    .045       0
   173.6      .1       0
#XS Ineff= 2 , 0
           100.7 2485.96
Permanent Ineff=
       F       F
Bank Sta=153.9,173.6
XS Rating Curve= 0 ,0
Exp/Cntr(USF)=0,0
Exp/Cntr=0.3,0.1

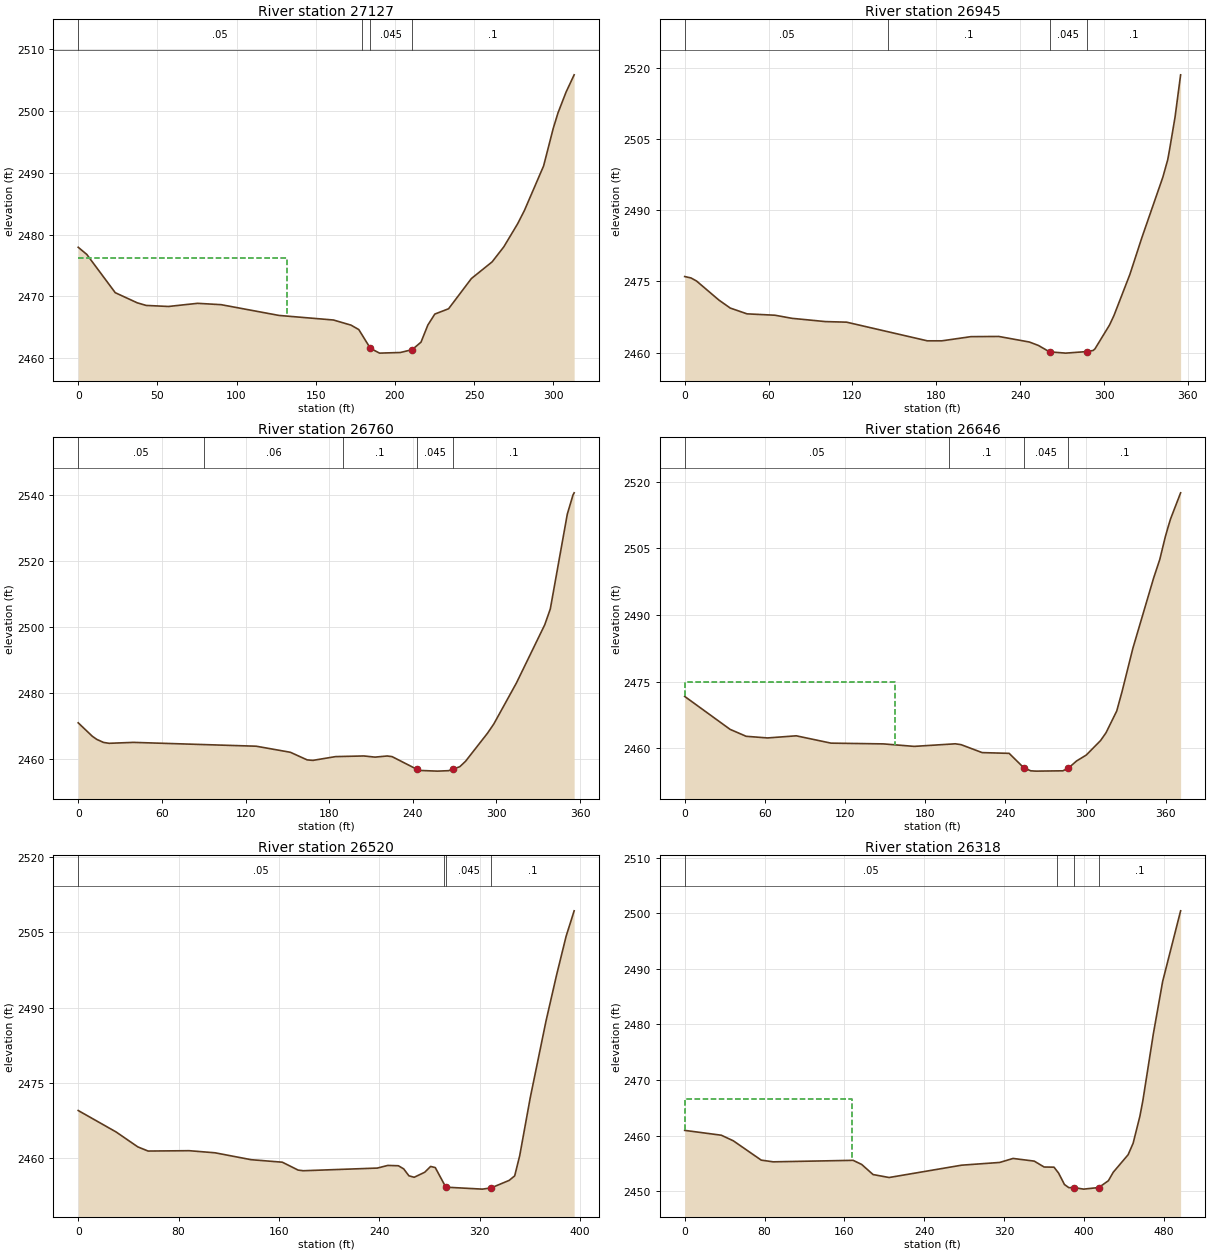
Type RM Length L Ch R = 1 ,27127   ,170.4,182.6,192.1
XS GIS Cut Line= 3
2249479.77563528494657.7353434932249433.09839361494582.042519154
2249227.46622082 494492.47267702
#Sta/Elev= 30
       0 2477.95     5.4  2476.8    23.4  2470.6    37.3 2468.96    42.9 2468.54
      57 2468.37    75.4 2468.88    90.3 2468.66   126.8 2466.92   161.2 2466.18
   172.3 2465.35   177.2 2464.63   184.5  2461.6   190.3 2460.82   203.4 2460.92
   210.9 2461.38   216.5  2462.6   220.8 2465.36   225.2 2467.14   233.9    2468
   248.3 2472.89   261.4 2475.59   268.8 2478.03   277.5 2481.75   281.8 2483.91
   293.9 2491.11     300  2497.2     303  2499.7   308.1 2503.07   313.2 2505.86
#Mann= 4 ,-1,0
       0     .05       0  178.93      .1       0   184.5    .045       0
   210.9      .1       0
#XS Ineff= 2 , 0
          131.98 2476.22
Permanent Ineff=
       F       F
Bank Sta=184.5,210.9
XS Rating Curve= 0 ,0
Exp/Cntr(USF)=0,0
Exp/Cntr=0.3,0.1

Type RM Length L Ch R = 1 ,26945   ,171.5,184.8,196.1
XS GIS Cut Line= 3
2249527.39239993494641.6612609122249536.54525354494506.349694816
2249396.08834002494338.144753594
#Sta/Elev= 30
       0 2476.04     4.5 2475.74     8.5 2475.09    24.5 2471.08    32.6  2469.4
    44.6 2468.18    64.6 2467.89    76.7 2467.24   100.7 2466.55   115.8 2466.43
   173.6  2462.5     184  2462.5   204.8 2463.38   224.7 2463.42   246.6 2462.25
   253.1 2461.52     261 2460.18   272.6 2459.91287.84012460.242   292.2 2460.47
   293.5  2460.8   303.9 2465.81   307.1 2467.82   318.5 2476.48     327 2484.16
   342.1 2496.97   345.6 2500.66   346.9 2502.78   350.8 2509.58   354.8 2518.51
#Mann= 4 ,-1,0
       0     .05       0  145.62      .1       0     261    .045       0
287.8401      .1       0
Bank Sta=261,287.8401
XS Rating Curve= 0 ,0
Exp/Cntr(USF)=0,0
Exp/Cntr=0.3,0.1

Type RM Length L Ch R = 1 ,26760   ,113.7,114.3,115.6
XS GIS Cut Line= 2
2249657.65377248494587.0887074432249598.36106008494236.378621341
#Sta/Elev= 30
       0 2471.04    10.1 2466.98    13.3 2466.03    18.2  2465.1    22.2 2464.84
    39.6 2465.12   127.7 2463.96   152.2 2462.12   164.2 2459.82   168.3 2459.67
   184.5 2460.81   204.8 2461.01   212.9 2460.66   221.6    2461   225.1 2460.81
   242.92456.978   245.3 2456.62   257.5 2456.42   265.6 2456.55     269 2457.05
   273.7 2457.76   277.8  2459.4   293.5 2467.87   298.1 2470.71   314.3  2483.1
   334.6 2500.71   338.6 2505.51   350.8 2534.22   354.9 2540.03   355.7 2540.65
#Mann= 5 ,-1,0
       0     .05       0      90     .06       0     190      .1       0
   242.9    .045       0     269      .1       0
Bank Sta=242.9,269
XS Rating Curve= 0 ,0
Exp/Cntr(USF)=0,0
Exp/Cntr=0.3,0.1

Type RM Length L Ch R = 1 ,26646   ,130.8,125.5,120.4
XS GIS Cut Line= 4
2249789.15195119494583.1027768072249793.33917124494515.440275237
2249737.02998977 494394.165251442249717.24376807494225.733861595
#Sta/Elev= 30
       0 2471.67      34 2464.25      46 2462.69      62 2462.32    83.5  2462.8
   109.5 2461.15   148.7 2460.98   171.7 2460.42   202.5    2461   206.8 2460.81
   222.6 2459.02   242.8 2458.85   253.6 2455.65   258.9 2454.92   262.9 2454.85
     283 2454.92   287.1 2455.53   293.3 2457.15   300.5 2458.47   311.2 2461.73
   315.3  2463.5   323.3 2468.39   327.3 2472.78   335.4 2482.53   350.9 2498.32
   355.5 2502.49   359.6 2507.55   361.7 2509.77   363.6 2511.65   371.1  2517.5
#Mann= 4 ,-1,0
       0     .05       0  197.79      .1       0   253.6    .045       0
   287.1      .1       0
#XS Ineff= 2 , 0
           157.3 2474.95
Permanent Ineff=
       F       F
Bank Sta=253.6,287.1
XS Rating Curve= 0 ,0
Exp/Cntr(USF)=0,0
Exp/Cntr=0.3,0.1

Type RM Length L Ch R = 1 ,26520   ,209.9,201.9,194
XS GIS Cut Line= 3
2249862.20303432494583.4125357392249896.51158592494435.673975736
2249821.42482989494203.952265131
#Sta/Elev= 30
       0  2469.5    30.2 2465.23    47.5 2462.26    55.7 2461.43    88.5  2461.5
   109.1 2461.08   137.8 2459.71   162.7 2459.21   175.3 2457.64   179.3 2457.51
   238.4 2458.04   246.8 2458.57   255.2  2458.5   259.4 2457.89   263.6  2456.5
   267.8 2456.21   276.2 2457.21   280.9 2458.37   284.6 2458.14     293 2454.24
   322.2 2453.85   329.2  2454.1   343.5 2455.59   347.9 2456.49   351.9  2460.5
   360.3 2472.04   372.9 2487.35   381.3 2496.48   388.9 2504.19   395.3 2509.25
#Mann= 4 ,-1,0
       0     .05       0  291.67      .1       0     293    .045       0
   329.2      .1       0
Bank Sta=293,329.2
XS Rating Curve= 0 ,0
Exp/Cntr(USF)=0,0
Exp/Cntr=0.3,0.1

Type RM Length L Ch R = 1 ,26318   ,155.6,155,154.4
XS GIS Cut Line= 3
2250189.78711909494545.8296188762250186.33472728494412.540868872
2249972.10972866494118.639258743
#Sta/Elev= 30
       0 2460.95    36.7 2460.08    48.7 2459.08    76.7  2455.6    88.7 2455.29
   168.8 2455.56   177.4 2454.82   188.8    2453   204.9 2452.47   277.6 2454.69
   315.7 2455.18   329.1  2455.9   350.3 2455.42   360.2 2454.36   370.1 2454.33
   374.7 2453.27   380.6 2451.21     385 2450.64   389.9 2450.67   399.8 2450.38
     415 2450.67   424.6 2451.89   429.5 2453.42   444.4 2456.57   449.4 2458.63
   456.2  2463.5   459.2 2466.34   469.7 2478.35     479 2487.75     497 2500.45
#Mann= 4 ,-1,0
       0     .05       0  373.33      .1       0   389.9    .045       0
     415      .1       0
#XS Ineff= 2 , 0
          167.33  2466.6
Permanent Ineff=
       F       F
Bank Sta=389.9,415
XS Rating Curve= 0 ,0
Exp/Cntr(USF)=0,0
Exp/Cntr=0.3,0.1