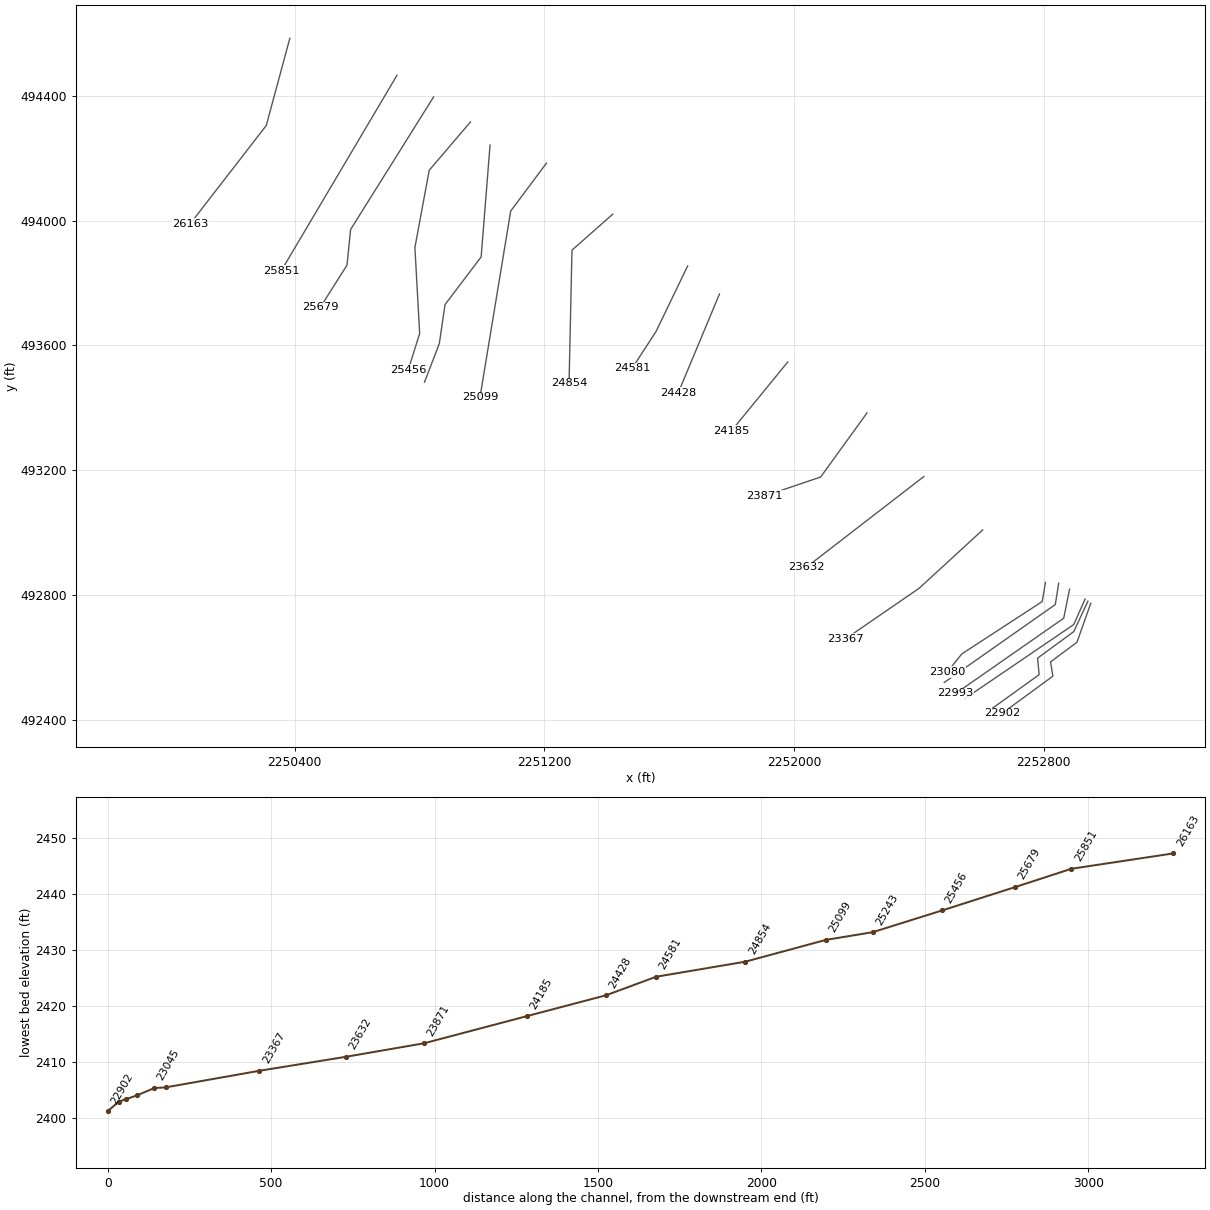
HEC-RAS study CLOVERCK.prj: CLOVERCK

--- CLOVERCK.g01 (geometry) --- (continued)

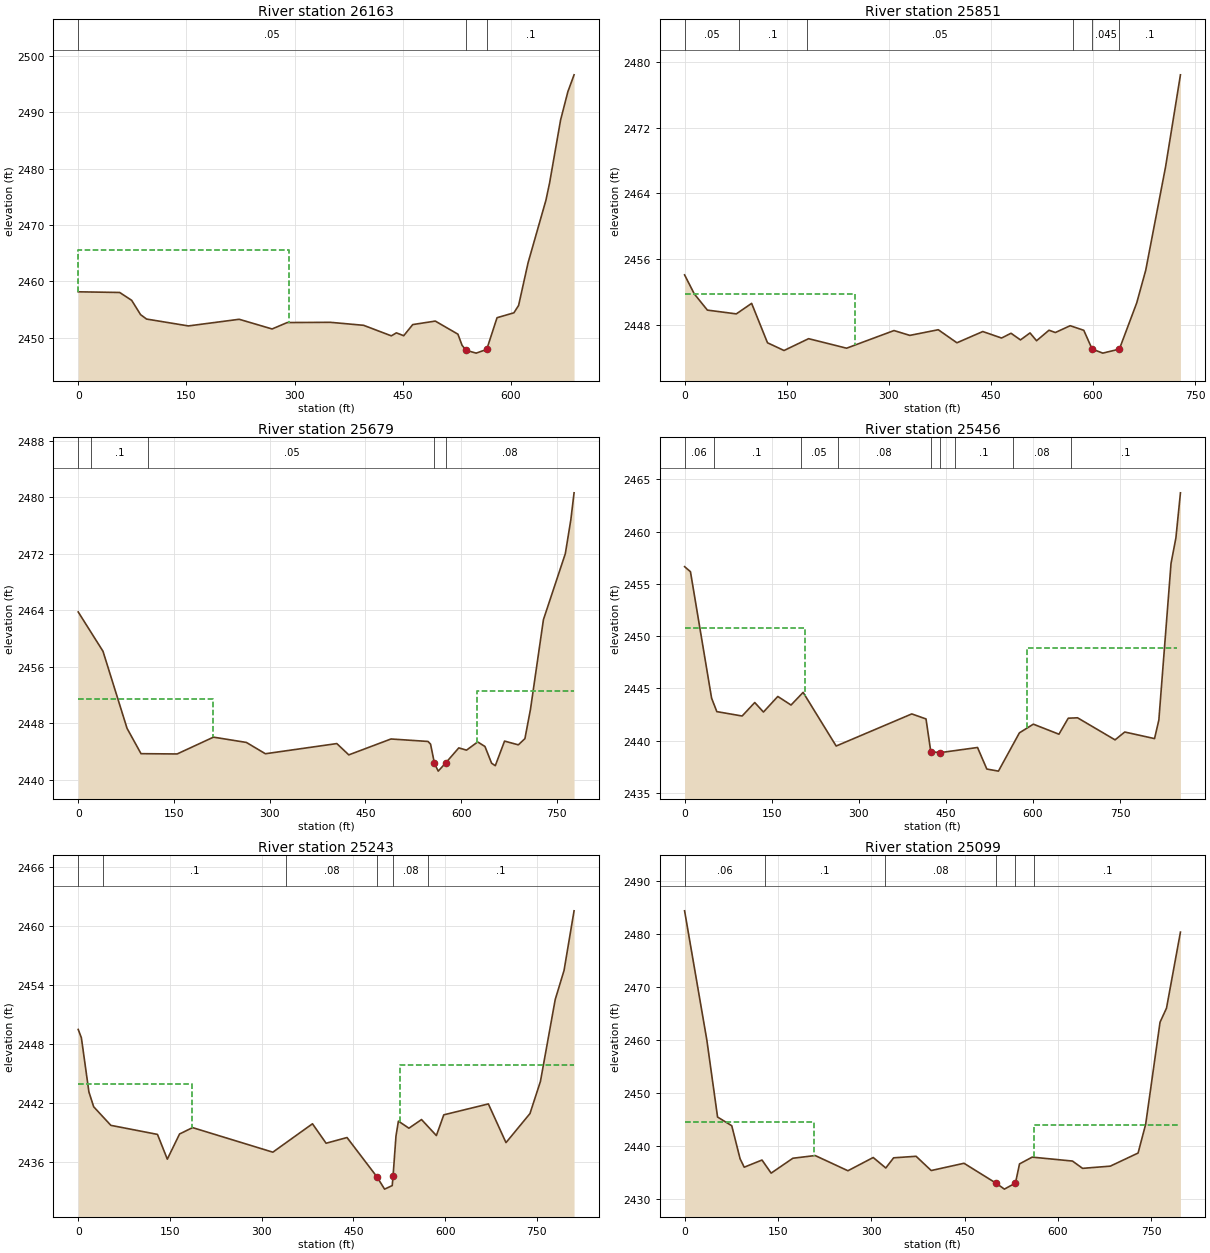
Type RM Length L Ch R = 1 ,26163   ,309.2,312.1,315.2
XS GIS Cut Line= 3
2250384.08964389494584.6685834772250308.60978314494305.151711274
2250065.13347684493990.376942241
#Sta/Elev= 30
       0 2458.15    57.5 2458.03    74.1 2456.64    86.5 2454.09    94.8 2453.31
   152.8 2452.09   223.2 2453.27   268.8 2451.55   289.8 2452.69   349.7 2452.73
   395.7  2452.2   434.1 2450.33   441.2 2450.86   451.3 2450.35   463.8 2452.33
   495.1 2452.95   526.5 2450.62   532.2 2448.65   537.9 2447.76   551.8 2447.26
   566.4 2447.92   580.7 2453.55   604.1 2454.42   610.6 2455.73   623.7 2463.29
   648.5 2474.42   653.6 2477.51   668.8 2488.65   678.9 2493.68   687.5 2496.68
#Mann= 3 ,-1,0
       0     .05       0   537.9    .045       0   566.4      .1       0
#XS Ineff= 2 , 0
          291.96 2465.53
Permanent Ineff=
       F       F
Bank Sta=537.9,566.4
XS Rating Curve= 0 ,0
Exp/Cntr(USF)=0,0
Exp/Cntr=0.3,0.1

Type RM Length L Ch R = 1 ,25851   ,159.3,172.3,183.1
XS GIS Cut Line= 2
 2250727.4456898494465.9801885022250356.55085054493838.991293564
#Sta/Elev= 30
       0 2454.05    14.3 2451.73    33.5 2449.76      76  2449.3    98.5 2450.58
   121.8 2445.78   146.1 2444.84   182.2 2446.28     238 2445.12   307.7 2447.27
   330.9 2446.68   372.7 2447.37   400.1 2445.78   438.1 2447.15   465.7 2446.36
   479.6 2446.94   493.5 2446.13   507.5 2446.98   517.1 2446.03   535.4 2447.31
   544.7 2447.03   566.5 2447.86   586.5  2447.3   598.7 2445.02   614.4 2444.52
  638.78 2445.01   664.3 2450.65   677.5 2454.62   706.7 2467.24   728.5 2478.42
#Mann= 6 ,-1,0
       0     .05       0      80      .1       0     180     .05       0
     570      .1       0   598.7    .045       0  638.78      .1       0
#XS Ineff= 2 , 0
          251.04 2451.77
Permanent Ineff=
       F       F
Bank Sta=598.7,638.78
XS Rating Curve= 0 ,0
Exp/Cntr(USF)=0,0
Exp/Cntr=0.3,0.1

Type RM Length L Ch R = 1 ,25679   ,223.6,222.8,222
XS GIS Cut Line= 4
2250844.76956752494396.5950995252250578.90419544493971.580082506
2250567.32500022493857.074707602 2250481.4440107493721.667415839
#Sta/Elev= 30
       0 2463.78    38.8 2458.22    76.5 2447.31    98.4 2443.72     155 2443.68
   211.9 2446.06   263.5 2445.31   293.2 2443.71   405.1 2445.15   423.9 2443.55
     490  2445.8     548 2445.45     552 2445.07  558.13 2442.33     564 2441.25
   576.1 2442.45   596.2 2444.54   608.3 2444.22   625.8 2445.38   637.2 2444.74
   647.6 2442.37   653.4 2442.02   667.9  2445.5   689.5 2444.97   699.8 2445.85
   708.5 2449.99   728.8 2462.69   763.1 2472.03   771.7  2476.8   776.8 2480.64
#Mann= 5 ,-1,0
       0     .06       0      20      .1       0     110     .05       0
  558.13    .045       0   576.1     .08       0
#XS Ineff= 2 , 0
          211.23 2451.47  624.43         2452.59
Permanent Ineff=
       F       F
Bank Sta=558.13,576.1
XS Rating Curve= 0 ,0
Exp/Cntr(USF)=0,0
Exp/Cntr=0.3,0.1

Type RM Length L Ch R = 1 ,25456   ,217.9,213,205.6
XS GIS Cut Line= 5
2250963.04519284494316.5812110972250830.85276937494161.436776843
 2250784.9627808493913.8734063662250800.24632344493638.059965667
 2250763.6628765493521.725796316
#Sta/Elev= 30
       0 2456.64    10.1 2456.16    46.5 2444.07    55.5 2442.78    99.1 2442.36
   120.8 2443.65   135.8 2442.74   160.5 2444.23   183.3 2443.41   204.1 2444.62
     261 2439.49   391.2 2442.56   415.7 2442.08   423.92438.965     439 2438.85
   504.4 2439.35   520.4 2437.29   540.4 2437.09   576.5 2440.75   600.5 2441.58
   644.6 2440.62   660.6 2442.15   676.6 2442.19   741.2 2440.08   757.9 2440.83
   809.2  2440.2   816.6 2441.97   837.6 2456.95     846  2459.4   853.8  2463.7
#Mann= 9 ,-1,0
       0     .06       0      50      .1       0     200     .05       0
  263.83     .08       0   423.9    .045       0     439     .08       0
  465.61      .1       0  565.61     .08       0  665.61      .1       0
#XS Ineff= 2 ,-1
       0  208.14 2450.76  589.47  847.032448.823
Permanent Ineff=
       F       F
Bank Sta=423.9,439
XS Rating Curve= 0 ,0
Exp/Cntr=0.3,0.1

Type RM Length L Ch R = 1 ,25243   ,132.7,143.6,155.6
XS GIS Cut Line= 5
2251025.85022352494242.3734464422250997.25961805493883.561347801
 2250881.4676659 493730.601608542250863.27117505493605.724991501
2250815.70927332493481.863340957
#Sta/Elev= 30
       0 2449.45     5.2  2448.6    17.5 2443.09    25.3 2441.58    53.4 2439.69
   129.6 2438.77   145.7 2436.25   165.7 2438.81     187 2439.46   318.2 2436.96
     383 2439.85   405.3 2437.87   439.5 2438.45   488.22434.469   500.9  2433.2
   513.4 2433.56  514.822434.565   519.5 2438.58   523.5 2440.12   540.7  2439.4
   561.3 2440.28   585.6 2438.65   597.7 2440.76   670.6 2441.87   699.4 2437.93
   738.6 2440.89   755.7 2444.16   779.9  2452.5   794.3 2455.45   810.7 2461.52
#Mann= 6 ,-1,0
       0     .06       0      40      .1       0     340     .08       0
   488.2    .045       0  514.82     .08       0  571.79      .1       0
#XS Ineff= 2 , 0
          185.35 2443.85  525.32         2445.82
Permanent Ineff=
       F       F
Bank Sta=488.2,514.82
XS Rating Curve= 0 ,0
Exp/Cntr(USF)=0,0
Exp/Cntr=0.3,0.1

Type RM Length L Ch R = 1 ,25099   ,242.3,245.7,249.1
XS GIS Cut Line= 3
2251206.83357728494184.655191377 2251092.0327937494030.746448555
2250993.63212206493434.034683352
#Sta/Elev= 30
       0 2484.36    35.8 2459.94      53 2445.43    75.8 2443.79    89.2 2437.55
    95.8 2435.96   124.4 2437.31   139.1 2434.84     174 2437.65   209.8 2438.16
   262.5 2435.29   303.1 2437.79   323.3 2435.81   335.9 2437.73     372 2438.02
   396.3 2435.33     449  2436.7  500.41 2432.95   513.9 2431.82  531.652432.964
   538.2 2436.58   558.5 2437.86   623.3 2437.12   639.5 2435.74   684.1 2436.16
   728.7 2438.63   740.9 2444.06     764 2463.33   774.4 2465.99   796.8 2480.34
#Mann= 6 ,-1,0
       0     .06       0     130      .1       0  322.01     .08       0
  500.41    .045       0  531.65     .08       0  562.01      .1       0
#XS Ineff= 2 , 0
          208.23 2444.47  560.87         2443.94
Permanent Ineff=
       F       F
Bank Sta=500.41,531.65
XS Rating Curve= 0 ,0
Exp/Cntr(USF)=0,0
Exp/Cntr=0.3,0.1

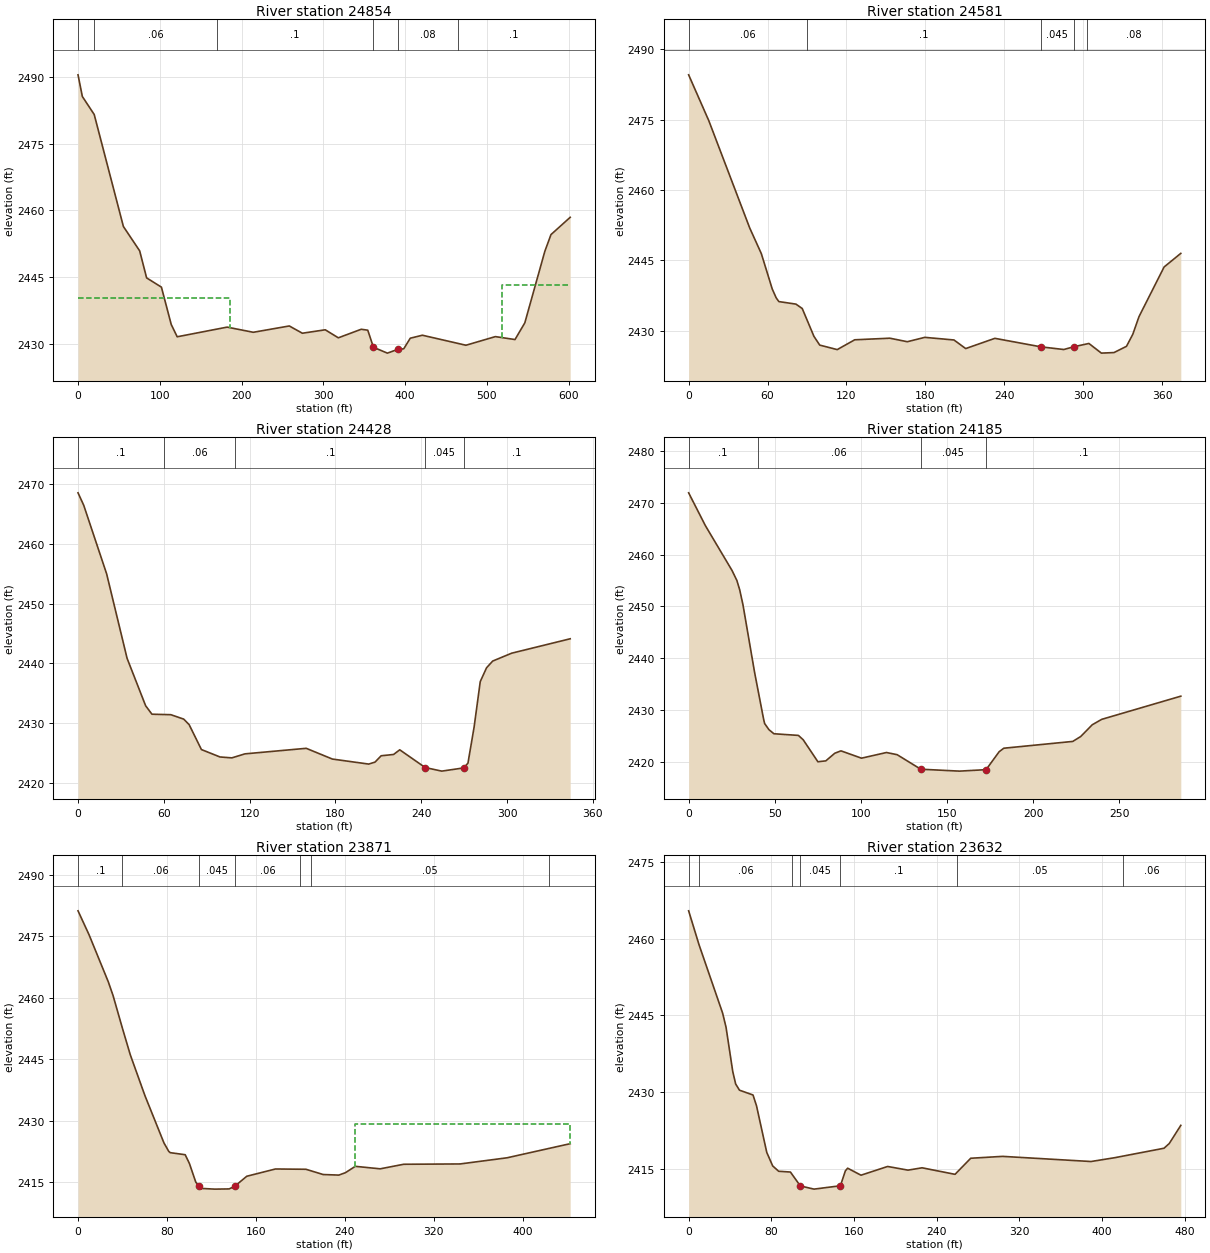
Type RM Length L Ch R = 1 ,24854   ,284.6,273.1,257.9
XS GIS Cut Line= 3
2251419.01097307494020.7199042512251288.40369645493905.220591184
2251278.97665338493477.688484593
#Sta/Elev= 30
       0 2490.44     5.3 2485.57    19.8 2481.53    55.5 2456.38    75.4 2450.91
    83.9 2444.84     102 2442.76     114 2434.38   121.3 2431.61   182.4 2433.78
   214.4 2432.62   258.4 2434.04   274.4 2432.41   302.4 2433.18   318.4 2431.38
   346.4  2433.3   354.4 2433.09  361.362429.252   378.4 2427.94     391 2428.78
   398.4 2428.91   406.4 2431.29   421.2 2431.96   474.5 2429.71   510.5 2431.65
   534.5 2430.99   546.5 2434.74     571 2450.81   578.5 2454.56     602 2458.44
#Mann= 6 ,-1,0
       0      .1       0      20     .06       0     170      .1       0
  361.36    .045       0     391     .08       0  464.35      .1       0
#XS Ineff= 2 , 0
          186.14  2440.4  518.99         2443.32
Permanent Ineff=
       F       F
Bank Sta=361.36,391
XS Rating Curve= 0 ,0
Exp/Cntr=0.3,0.1

Type RM Length L Ch R = 1 ,24581   ,148.8,152.9,157.1
XS GIS Cut Line= 3
2251659.25463368493855.0116635732251558.25281712493645.192319913
2251481.29826037493526.571737351
#Sta/Elev= 30
       0 2484.53    15.4 2474.72    46.4 2451.94    55.3 2446.43    63.6  2438.9
    66.6 2437.02    68.6 2436.23    81.6 2435.69    86.4 2434.75    95.3 2428.82
    99.7 2426.96     113    2426   126.3 2428.09     153 2428.43   166.3 2427.68
   179.6 2428.61   201.8 2428.05   210.7 2426.22   232.9  2428.4267.96972426.586
   285.3 2426.02292.85472426.602   304.4 2427.31   313.9 2425.25   323.5 2425.37
     333  2426.7   337.8 2429.27   342.5 2433.02   361.6  2443.6   374.3  2446.5
#Mann= 5 ,-1,0
       0     .06       0      90      .1       0267.9697    .045       0
292.8547      .1       0  302.86     .08       0
Bank Sta=267.9697,292.8547
XS Rating Curve= 0 ,0
Exp/Cntr(USF)=0,0
Exp/Cntr=0.3,0.1

Type RM Length L Ch R = 1 ,24428   ,250.5,242.7,234.1
XS GIS Cut Line= 2
2251761.12709099493764.8829322532251628.74252167493447.159965893
#Sta/Elev= 30
       0 2468.55       4 2466.46      20 2454.99    34.3 2440.85    47.3 2432.89
    51.7 2431.48    64.9  2431.4    73.9 2430.66    77.7 2429.74    86.3 2425.56
    99.3 2424.32   107.6 2424.17   116.7 2424.84   159.6 2425.77   177.9 2423.97
   203.3 2423.13   207.7 2423.46     212 2424.52   220.7 2424.74     225 2425.52
   242.8 2422.55   254.4 2421.95   269.7 2422.49   272.7 2423.28     277 2429.32
   281.3 2436.94   285.7 2439.25     290 2440.38   303.3  2441.7   344.2 2444.11
#Mann= 5 ,-1,0
       0      .1       0      60     .06       0     110      .1       0
   242.8    .045       0   269.7      .1       0
Bank Sta=242.8,269.7
XS Rating Curve= 0 ,0
Exp/Cntr(USF)=0,0
Exp/Cntr=0.3,0.1

Type RM Length L Ch R = 1 ,24185   ,312.3,314.1,316.7
XS GIS Cut Line= 2
 2251980.0870154493546.8491806752251799.42101492 493325.68907664
#Sta/Elev= 30
       0 2471.91     9.7 2465.59    25.2 2456.92      28 2454.99    29.6 2453.24
    31.5 2450.36    38.3 2437.22    43.5 2428.25    44.1  2427.4    46.6 2426.22
    49.5 2425.43    63.7 2425.11    66.5 2424.26      75 2420.03    79.6  2420.2
    84.8 2421.67    88.4 2422.13   100.3 2420.72   114.8 2421.81     121 2421.39
   134.7 2418.59   157.1 2418.22   172.6  2418.5   180.2 2421.97   182.9 2422.64
   222.9 2423.95   227.5 2424.89   234.2 2427.16   239.7 2428.21   285.6 2432.68
#Mann= 4 ,-1,0
       0      .1       0      40     .06       0   134.7    .045       0
   172.6      .1       0
Bank Sta=134.7,172.6
XS Rating Curve= 0 ,0
Exp/Cntr(USF)=0,0
Exp/Cntr=0.3,0.1

Type RM Length L Ch R = 1 ,23871   ,246.3,239,231.2
XS GIS Cut Line= 3
2252233.95389538493383.315300931 2252085.4336523493177.736323746
 2251906.3615745493116.964368781
#Sta/Elev= 30
       0 2481.24     9.9 2475.42    27.3 2463.88    31.5 2460.59      40 2452.55
      47 2446.15    60.1 2436.24    77.3 2424.64    81.6 2422.59      83 2422.27
    96.4 2421.77   100.2 2419.63   105.9  2415.1   108.8 2414.12   111.7 2413.54
   123.1 2413.38   135.9 2413.43   140.8 2414.04   151.8 2416.52   177.6 2418.29
     205 2418.22   220.5 2416.94   234.6  2416.8   240.6  2417.4   249.4 2418.94
   271.8 2418.33   292.9 2419.44   343.7 2419.52   385.9 2421.02   442.7 2424.46
#Mann= 7 ,-1,0
       0      .1       0      40     .06       0   108.8    .045       0
   140.8     .06       0     200      .1       0     210     .05       0
  423.62      .1       0
#XS Ineff= 2 , 0
                          248.76         2429.29
Permanent Ineff=
       F       F
Bank Sta=108.8,140.8
XS Rating Curve= 0 ,0
Exp/Cntr(USF)=0,0
Exp/Cntr=0.3,0.1

Type RM Length L Ch R = 1 ,23632   ,263.7,265.1,268.6
XS GIS Cut Line= 2
2252416.17736138493179.2873176312252039.27070521492888.041265135
#Sta/Elev= 30
       0 2465.51    10.1 2458.84    32.9 2445.46    36.2 2442.69    42.7 2434.01
    45.5 2431.58    49.2 2430.36    62.3 2429.42    65.7 2427.29    75.6 2418.17
    81.3 2415.53    87.1 2414.47    98.5 2414.32   108.1  2411.6   121.3 2410.97
   146.9 2411.63   151.7 2414.56   153.9 2415.07   166.8  2413.7   192.6 2415.41
   212.3 2414.69   225.9 2415.15   257.8 2413.87     273 2417.02   303.8 2417.39
   389.4 2416.38   412.1 2417.12     460 2418.98   465.1  2419.9   476.3 2423.47
#Mann= 7 ,-1,0
       0      .1       0      10     .06       0     100     .08       0
   108.1    .045       0   146.9      .1       0     260     .05       0
     420     .06       0
Bank Sta=108.1,146.9
XS Rating Curve= 0 ,0
Exp/Cntr(USF)=0,0
Exp/Cntr=0.3,0.1

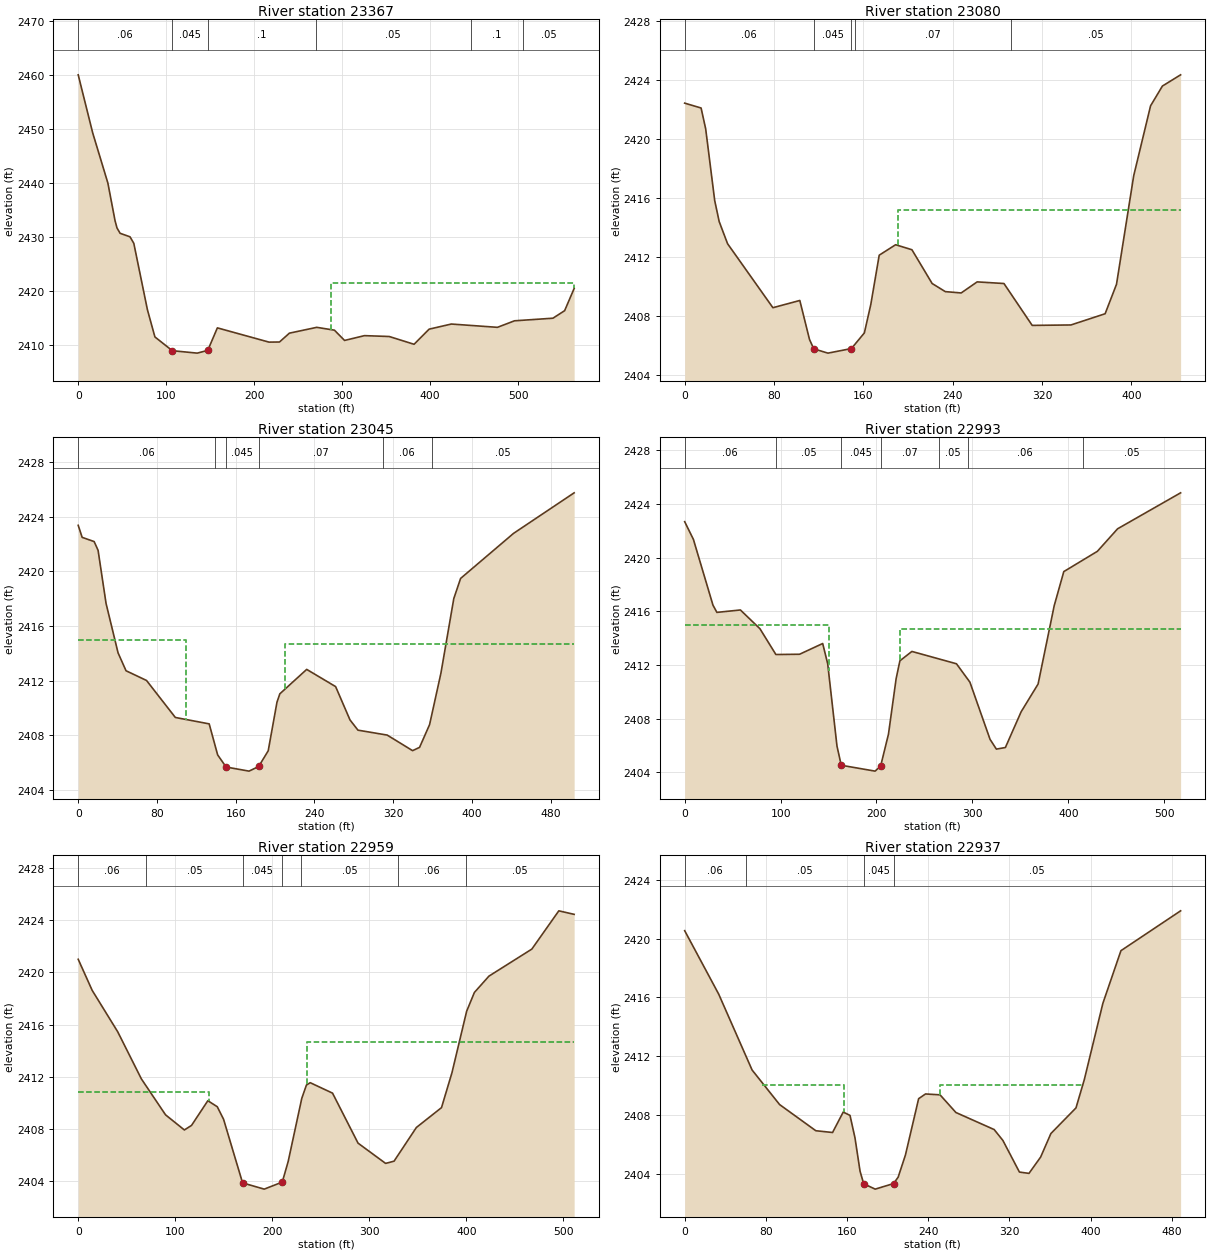
Type RM Length L Ch R = 1 ,23367   ,294,286.6,286.3
XS GIS Cut Line= 3
2252604.63068947493007.9661102812252401.46301445492821.194245801
2252164.36566574 492658.02849204
#Sta/Elev= 30
       0 2460.04    16.4 2449.32    33.7    2440    41.9 2432.99    44.1 2431.66
    47.6 2430.68    58.9 2430.02    63.2 2428.82    78.7  2416.5    87.2 2411.47
     107 2408.92   135.3 2408.47   147.3 2408.98   158.2 2413.15   216.9 2410.51
   228.8 2410.53   240.1 2412.17   271.2 2413.25   291.3 2412.72   302.8 2410.82
   325.4 2411.71   353.6 2411.55   381.8 2410.11   398.9 2412.91   424.2 2413.86
   476.6 2413.25     496 2414.46   539.7 2414.94     553 2416.34   563.8 2420.45
#Mann= 6 ,-1,0
       0     .06       0     107    .045       0   147.3      .1       0
     270     .05       0  445.97      .1       0  505.97     .05       0
#XS Ineff= 2 , 0
                          287.79         2421.47
Permanent Ineff=
       F       F
Bank Sta=107,147.3
XS Rating Curve= 0 ,0
Exp/Cntr(USF)=0,0
Exp/Cntr=0.3,0.1

Type RM Length L Ch R = 1 ,23080   ,33.5,35.2,35.4
BEGIN DESCRIPTION:
xs 4
END DESCRIPTION:
XS GIS Cut Line= 4
2252805.82252805492839.7022077482252795.60399677492778.391020034
2252537.86992989492610.3529500022252491.31884292492552.447939383
#Sta/Elev= 30
       0 2422.46    14.7 2422.13    18.8 2420.72    26.9 2415.85    30.9 2414.43
    38.4 2412.93      79 2408.59   103.1 2409.08   111.8 2406.43   115.6  2405.8
   128.3 2405.51   149.3 2405.82   160.9 2406.88   166.7 2408.82   174.2 2412.15
   188.9 2412.86   203.5 2412.52   221.6 2410.23   233.4 2409.68   247.6 2409.59
   261.9 2410.34   285.9 2410.23   311.2 2407.39   345.9 2407.42   376.5 2408.18
   386.7 2410.18   402.1 2417.54   417.2 2422.28   427.8 2423.62   444.1 2424.38
#Mann= 5 ,-1,0
       0     .06       0   115.6    .045       0   149.3     .06       0
  152.16     .07       0  292.16     .05       0
#XS Ineff= 2 , 0
                          191.03         2415.19
Permanent Ineff=
       F       F
Bank Sta=115.6,149.3
XS Rating Curve= 0 ,0
Exp/Cntr(USF)=0,0
Exp/Cntr=0.5,0.3

Type RM Length L Ch R = 1 ,23045   ,52,51.6,51
BEGIN DESCRIPTION:
xs 3
END DESCRIPTION:
XS GIS Cut Line= 3
2252848.33666439492837.1791136042252837.48735957492768.677107577
2252481.73108517 492518.89078726
#Sta/Elev= 30
       0 2423.38       4  2422.5    16.2 2422.19    20.2 2421.55    28.3 2417.66
    40.5 2414.04    48.6 2412.73    69.4 2412.02    98.7 2409.31   133.1 2408.84
   141.7 2406.57   150.3 2405.68   173.6 2405.38   183.4 2405.72   193.1 2406.87
     202 2410.43   204.9 2411.04   232.2 2412.83   261.6 2411.57   276.2 2409.13
   284.3 2408.38     314 2408.02   339.8 2406.88   346.9 2407.12   357.1 2408.79
   368.6 2412.55   381.7 2418.02   388.6 2419.49   442.4 2422.79     504 2425.76
#Mann= 6 ,-1,0
       0     .06       0  139.36     .07       0   150.3    .045       0
   183.4     .07       0  309.36     .06       0  359.36     .05       0
#XS Ineff= 2 , 0
             110    2415     210          2414.7
Permanent Ineff=
       F       F
Bank Sta=150.3,183.4
XS Rating Curve= 0 ,0
Exp/Cntr(USF)=0,0
Exp/Cntr=0.5,0.3

Type RM Length L Ch R = 1 ,22993   ,34.4,34.5,33.8
BEGIN DESCRIPTION:
xs 2
END DESCRIPTION:
XS GIS Cut Line= 3
2252883.15536358492818.1297528122252864.48446691492724.901424168
2252518.31595027492483.567469235
#Sta/Elev= 30
       0 2422.69     9.1 2421.37    29.5 2416.47    33.6 2415.93    58.1 2416.11
    78.5 2414.71    95.1 2412.79   119.8 2412.81   143.9 2413.61   149.1 2412.11
   158.8 2405.97  163.242404.538   198.5  2404.1   204.3 2404.47   212.5 2406.86
   220.5    2411   224.4 2412.32   236.9 2413.02   283.4  2412.1   297.4 2410.73
   318.4 2406.47     325 2405.74   334.4 2405.86   350.8 2408.52   368.5 2410.59
   385.3 2416.43   395.3 2418.97   430.3 2420.48   451.4 2422.16   517.1 2424.84
#Mann= 7 ,-1,0
       0     .06       0   95.08     .05       0  163.24    .045       0
   204.3     .07       0  265.08     .05       0  295.08     .06       0
  415.08     .05       0
#XS Ineff= 2 , 0
             150    2415     225          2414.7
Permanent Ineff=
       F       F
Bank Sta=163.24,204.3
XS Rating Curve= 0 ,0
Exp/Cntr(USF)=0,0
Exp/Cntr=0.5,0.3

Type RM Length L Ch R = 1 ,22959   ,20.9,22.3,24.5
BEGIN DESCRIPTION:
xs 4
END DESCRIPTION:
XS GIS Cut Line= 3
2252932.98647294 492786.338766592252896.65391726492704.590516304
2252548.08846118492467.293512002
#Sta/Elev= 30
       0 2421.01    14.4 2418.63    40.7 2415.46    65.1 2411.85      90  2409.1
   109.4 2407.94   116.8 2408.29   133.6 2410.18   143.3 2409.72   149.8 2408.76
   169.42403.887   191.7 2403.41   210.3 2403.95   216.4 2405.53   230.4 2410.36
   235.2 2411.38   239.1 2411.56   262.1 2410.76   288.4 2406.93   316.8 2405.38
   325.5 2405.55   348.5 2408.13   374.4 2409.65   385.2 2412.33   400.3 2417.03
   408.3 2418.47   423.3 2419.72   467.5 2421.79   495.3 2424.72   511.1 2424.45
#Mann= 7 ,-1,0
       0     .06       0      70     .05       0   169.4    .045       0
   210.3     .07       0  229.46     .05       0  329.46     .06       0
  399.46     .05       0
#XS Ineff= 2 , 0
          134.55 2410.85  236.21          2414.7
Permanent Ineff=
       F       F
Bank Sta=169.4,210.3
XS Rating Curve= 0 ,0
Exp/Cntr(USF)=0,0
Exp/Cntr=0.5,0.3

Type RM Length L Ch R = 1 ,22937   ,33.9,34.1,34.9
BEGIN DESCRIPTION:
xs 3
END DESCRIPTION:
XS GIS Cut Line= 5
2252942.06961186492779.5264123992252896.65391726492681.882669002
2252780.63779453492596.7103628682252785.68683075492543.803255474
2252636.47236035492436.447270186
#Sta/Elev= 30
       0 2420.54    33.5 2416.23    66.4 2411.07    93.5 2408.72   129.2 2406.94
   145.7 2406.82   156.2 2408.21   162.9 2407.98   167.8 2406.45   172.8 2404.18
176.38852403.332   187.7 2402.97205.78372403.349   210.3 2403.78   217.5 2405.29
   230.5 2409.12   237.3 2409.44   251.6 2409.38   267.2 2408.18   304.9 2407.02
   313.5 2406.28   329.8 2404.13   339.2 2404.04   350.7 2405.15   360.8 2406.75
   385.5 2408.49   393.7 2410.41     412  2415.6   429.8 2419.18   488.6 2421.89
#Mann= 4 ,-1,0
       0     .06       0      60     .05       0176.3885    .045       0
205.7837     .05       0
#XS Ineff= 4 ,-1
   75.97   156.9 2410.06     157     162    2405     230  251.74    2405
  251.74  393.74 2410.02
Permanent Ineff=
       F       F       F       F
Bank Sta=176.3885,205.7837
XS Rating Curve= 0 ,0
Exp/Cntr(USF)=0,0
Exp/Cntr=0.5,0.3

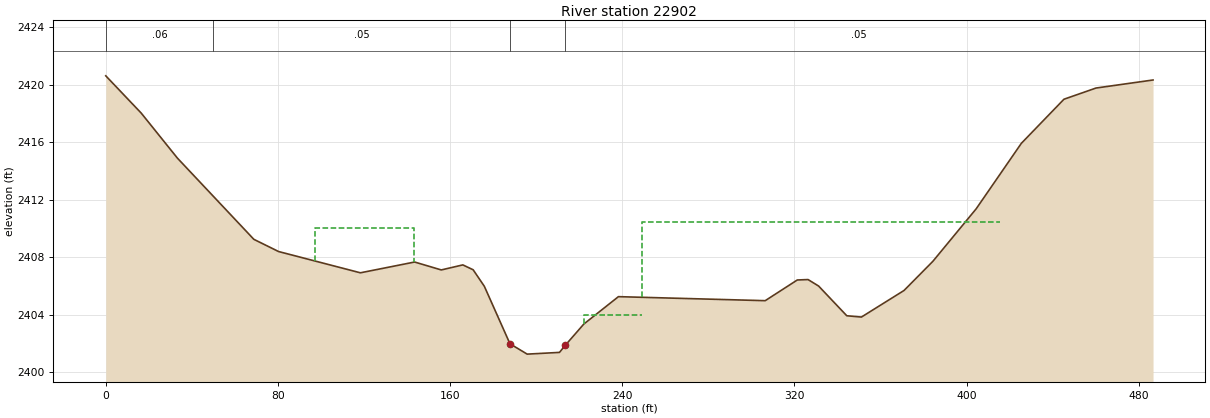
Type RM Length L Ch R = 1 ,22902   ,94.8,92.8,92.4
BEGIN DESCRIPTION:
xs 2
END DESCRIPTION:
XS GIS Cut Line= 5
2252951.15275078492772.7140582092252906.87244854492647.669402647
 2252822.1507515492584.7386514232252829.75014693492538.881242947
 2252666.8053808 492419.66895797
#Sta/Elev= 30
       0 2420.62    16.5 2418.02    33.3 2414.89    68.8 2409.24    80.3 2408.39
   118.3 2406.91   143.5 2407.66   155.9 2407.11   165.9 2407.46   170.7 2407.12
   175.9 2405.97187.80752401.969   195.8 2401.25   210.8 2401.37213.56432401.874
   222.1 2403.34   238.2 2405.25   306.4 2404.97   321.3 2406.41   326.3 2406.44
   331.2 2405.99   344.3 2403.92   351.1 2403.83   370.9 2405.68   384.3 2407.71
   404.4 2411.36   425.4 2415.92   445.2 2418.99   460.1 2419.77   486.6 2420.33
#Mann= 4 ,-1,0
       0     .06       0      50     .05       0187.8075    .045       0
213.5643     .05       0
#XS Ineff= 4 ,-1
      97     143    2410     143     172    2404     222  249.26    2404
  249.26  415.59 2410.42
Permanent Ineff=
       F       F       F       F
Bank Sta=187.8075,213.5643
XS Rating Curve= 0 ,0
Exp/Cntr(USF)=0,0
Exp/Cntr=0.5,0.3