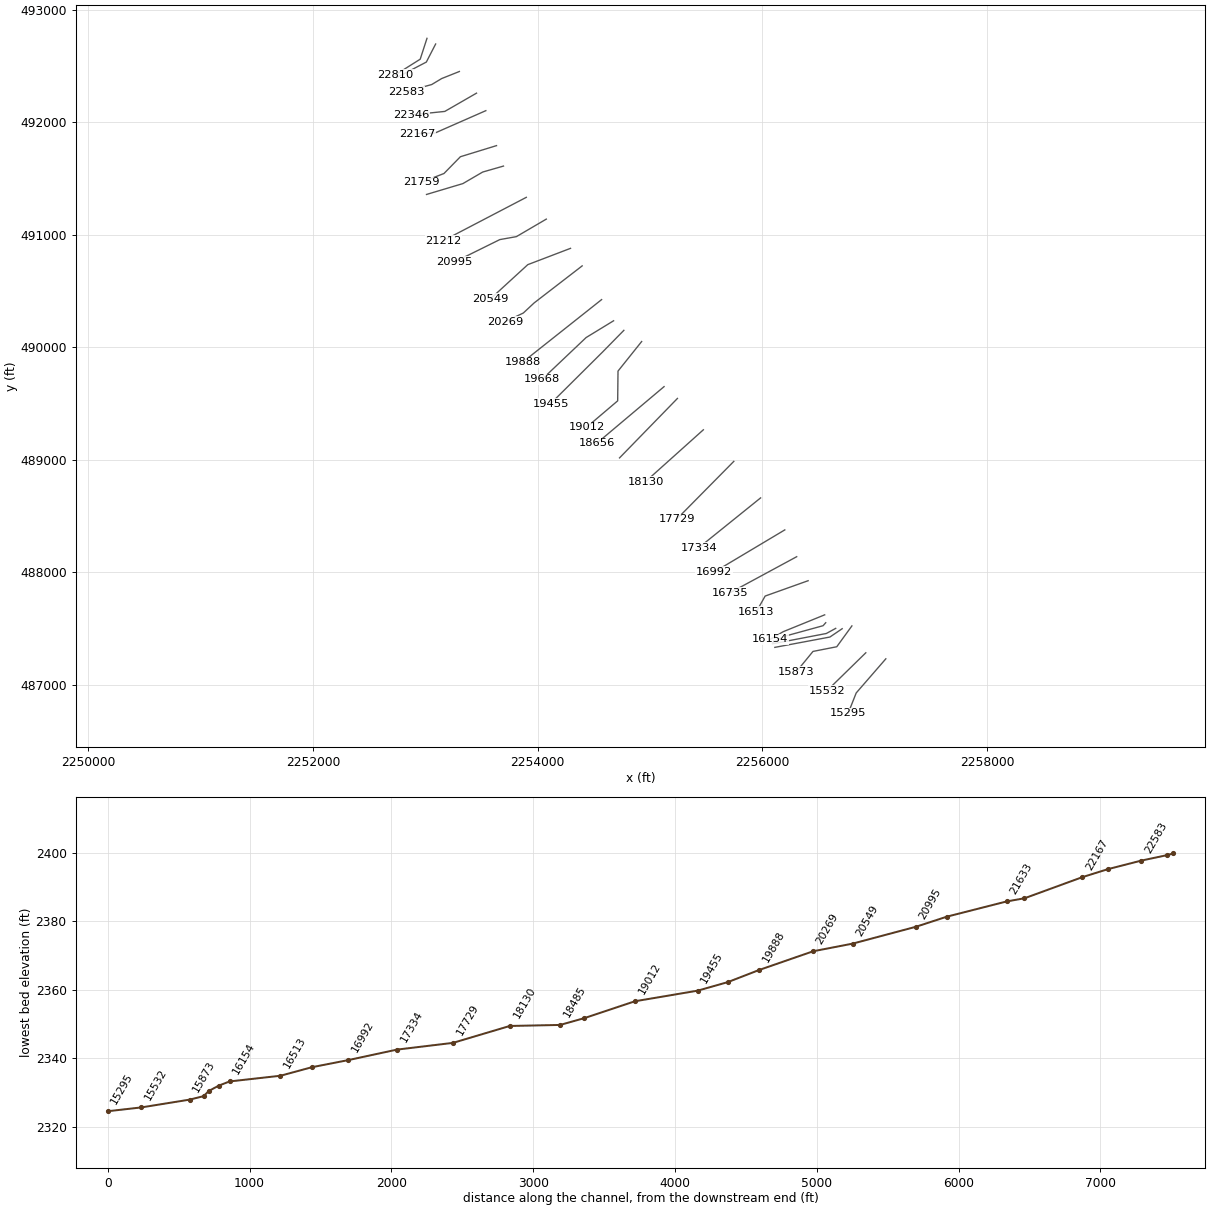
HEC-RAS study CLOVERCK.prj: CLOVERCK

--- CLOVERCK.g01 (geometry) --- (continued)

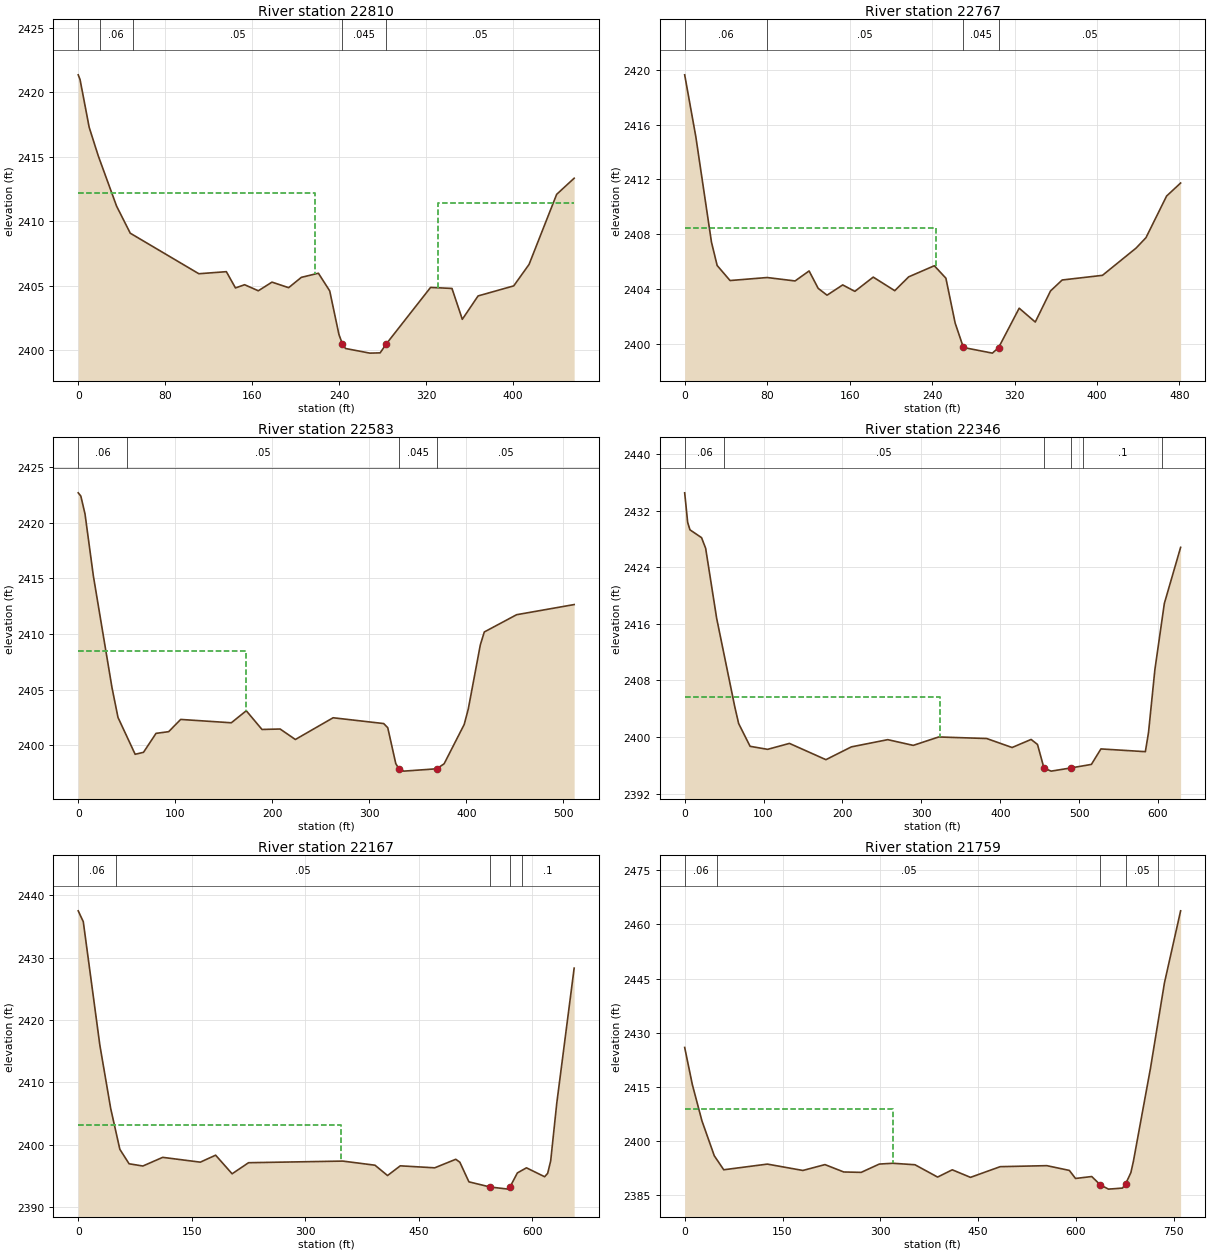
Type RM Length L Ch R = 1 ,22810   ,45.2,42.2,39.9
BEGIN DESCRIPTION:
xs 1
END DESCRIPTION:
XS GIS Cut Line= 3
2253014.46175179492746.779897828 2252954.2059479492561.321650967
2252733.09115362492422.098111642
#Sta/Elev= 30
       0 2421.35     1.7 2420.98    10.1 2417.28    18.5 2415.06    35.3 2411.18
    47.9 2409.08     111 2405.94   136.3  2406.1   144.7 2404.84   153.1 2405.09
   165.7 2404.62   178.3 2405.29   193.6 2404.86   205.3 2405.66     221 2405.98
   231.4 2404.61   239.9 2401.23     243 2400.53   245.9 2400.15   268.3 2399.79
   277.8 2399.81   283.6 2400.52   324.2 2404.88   343.9  2404.8   353.4 2402.41
   367.9 2404.22   400.7    2405   414.8 2406.66   440.2 2412.09   456.3 2413.34
#Mann= 5 ,-1,0
       0      .1       0      20     .06       0      50     .05       0
     243    .045       0   283.6     .05       0
#XS Ineff= 2 , 0
          217.97 2412.23   331.4         2411.39
Permanent Ineff=
       F       F
Bank Sta=243,283.6
XS Rating Curve= 0 ,0
Exp/Cntr=0.3,0.1

Type RM Length L Ch R = 1 ,22767   ,190.4,184.3,178.4
XS GIS Cut Line= 3
2253091.53254317492696.3084557552253008.63896419492535.751820218
2252742.39972626492396.684494025
#Sta/Elev= 30
       0 2419.63    10.8 2415.12      26 2407.41    31.5 2405.71      44 2404.61
      80 2404.83   107.1 2404.58   120.7 2405.31   129.5 2404.04   138.1 2403.54
   153.3 2404.29   165.1 2403.82   182.9 2404.86   203.8 2403.87   217.3 2404.88
   242.2 2405.69   253.4 2404.78   262.4  2401.5270.38852399.722   298.5 2399.31
   304.5 2399.71   324.5 2402.59   340.1 2401.58   354.9 2403.85   366.2 2404.65
   405.3 2404.99   437.9 2406.98   447.5 2407.74   467.5 2410.78   481.1 2411.73
#Mann= 4 ,-1,0
       0     .06       0      80     .05       0270.3885    .045       0
   304.5     .05       0
#XS Ineff= 2 , 0
          243.36 2408.48
Permanent Ineff=
       F       F
Bank Sta=270.3885,304.5
XS Rating Curve= 0 ,0
Exp/Cntr(USF)=0,0
Exp/Cntr=0.3,0.1

Type RM Length L Ch R = 1 ,22583   ,242.8,237.5,233.5
XS GIS Cut Line= 4
2253302.70911958 492451.900809772253145.53785107492389.238424804
2253056.49855185492335.8791335732252827.00916531492272.529338904
#Sta/Elev= 30
       0 2422.67     2.7 2422.38       7 2420.78    15.6 2415.22    34.8 2405.19
      41 2402.51    58.7  2399.2    67.3 2399.38    80.2 2401.08    93.2 2401.23
   105.6 2402.33   157.8 2402.03   173.2 2403.11   189.4 2401.43   208.1 2401.47
   223.8 2400.53   262.7 2402.48   314.8 2401.96     319 2401.59   327.3 2398.36
330.41092397.911   335.6 2397.69369.5105  2397.9   377.1 2398.35   397.8 2401.88
     402 2403.27   414.4 2409.02   418.5 2410.18   451.8 2411.73   511.1 2412.64
#Mann= 4 ,-1,0
       0     .06       0      50     .05       0330.4109    .045       0
369.5105     .05       0
#XS Ineff= 2 , 0
          173.39 2408.51
Permanent Ineff=
       F       F
Bank Sta=330.4109,369.5105
XS Rating Curve= 0 ,0
Exp/Cntr(USF)=0,0
Exp/Cntr=0.3,0.1

Type RM Length L Ch R = 1 ,22346   ,181.7,178.6,177
XS GIS Cut Line= 3
2253455.26113626492259.2992906672253173.18464404492096.893735645
2252871.72352869492065.471630426
#Sta/Elev= 30
       0 2434.52     3.8 2430.33     6.7 2429.29    21.4 2428.18    26.6 2426.67
    40.5  2416.8    63.6 2404.22    68.4  2401.9    82.9 2398.68   105.1 2398.25
   132.8 2399.09     179 2396.79   211.3  2398.6   257.4 2399.62   289.7 2398.81
     322    2400   382.8 2399.78     415 2398.51   439.1 2399.65   447.2 2398.94
   455.42395.602   464.5 2395.17   489.42395.617   515.5 2396.12   527.6 2398.31
   583.9 2397.92   587.9 2400.62     596 2409.53     608 2418.89   628.6 2426.81
#Mann= 6 ,-1,0
       0     .06       0      50     .05       0   455.4    .045       0
   489.4     .05       0  505.49      .1       0  605.49     .05       0
#XS Ineff= 2 , 0
          324.17  2405.7
Permanent Ineff=
       F       F
Bank Sta=455.4,489.4
XS Rating Curve= 0 ,0
Exp/Cntr(USF)=0,0
Exp/Cntr=0.3,0.1

Type RM Length L Ch R = 1 ,22167   ,397.2,407.9,416.9
XS GIS Cut Line= 3
2253538.32527389492103.5229219932253083.63980175491903.874853382
2252925.14131921 491900.28433345
#Sta/Elev= 30
       0 2437.52     6.7 2435.78    28.6 2415.95    42.9  2405.8      55 2399.24
    67.2 2396.92    85.4 2396.56   111.6 2397.95   161.3 2397.18   181.5  2398.3
   203.3 2395.31     225 2397.09   349.5 2397.35     392 2396.69   408.6 2395.03
   425.4 2396.59   470.9 2396.27   498.7 2397.64   504.1 2397.17   516.1 2394.02
   544.1 2393.19   568.1 2392.85  570.41 2393.21   580.1 2395.45   592.1 2396.27
   616.1 2394.84   620.1 2395.38   624.1 2397.38   632.1  2406.6   655.1 2428.32
#Mann= 5 ,-1,0
       0     .06       0      50     .05       0   544.1    .045       0
  570.41     .05       0  586.59      .1       0
#XS Ineff= 2 , 0
          347.04 2403.13
Permanent Ineff=
       F       F
Bank Sta=544.1,570.41
XS Rating Curve= 0 ,0
Exp/Cntr(USF)=0,0
Exp/Cntr=0.3,0.1

Type RM Length L Ch R = 1 ,21759   ,128.9,126.2,125.7
XS GIS Cut Line= 4
2253633.42846046491792.6552255542253311.85045278491693.863235733
2253165.67863111491544.6671694732252965.07040688491467.044891756
#Sta/Elev= 30
       0 2425.91    11.8 2415.59    26.4 2405.63    45.4 2395.92    59.9 2392.04
   126.8 2393.61   181.2 2391.85   215.1 2393.47   243.9 2391.43   270.6 2391.32
   298.4 2393.62   319.3 2393.84   353.1 2393.43   387.8 2390.02   410.3 2392.03
   438.2 2389.94   483.8  2392.9   555.3 2393.18   589.8 2391.86   599.3 2389.63
   624.1 2390.17   637.32387.859   649.8 2386.68   671.3 2386.97   675.9 2388.07
   684.1 2391.23     688 2394.38   714.2 2420.18   735.6 2443.79   760.4 2463.75
#Mann= 5 ,-1,0
       0     .06       0      50     .05       0   637.3    .045       0
   675.9     .05       0  725.28      .1       0
#XS Ineff= 2 , 0
          318.94 2408.78
Permanent Ineff=
       F       F
Bank Sta=637.3,675.9
XS Rating Curve= 0 ,0
Exp/Cntr(USF)=0,0
Exp/Cntr=0.3,0.1

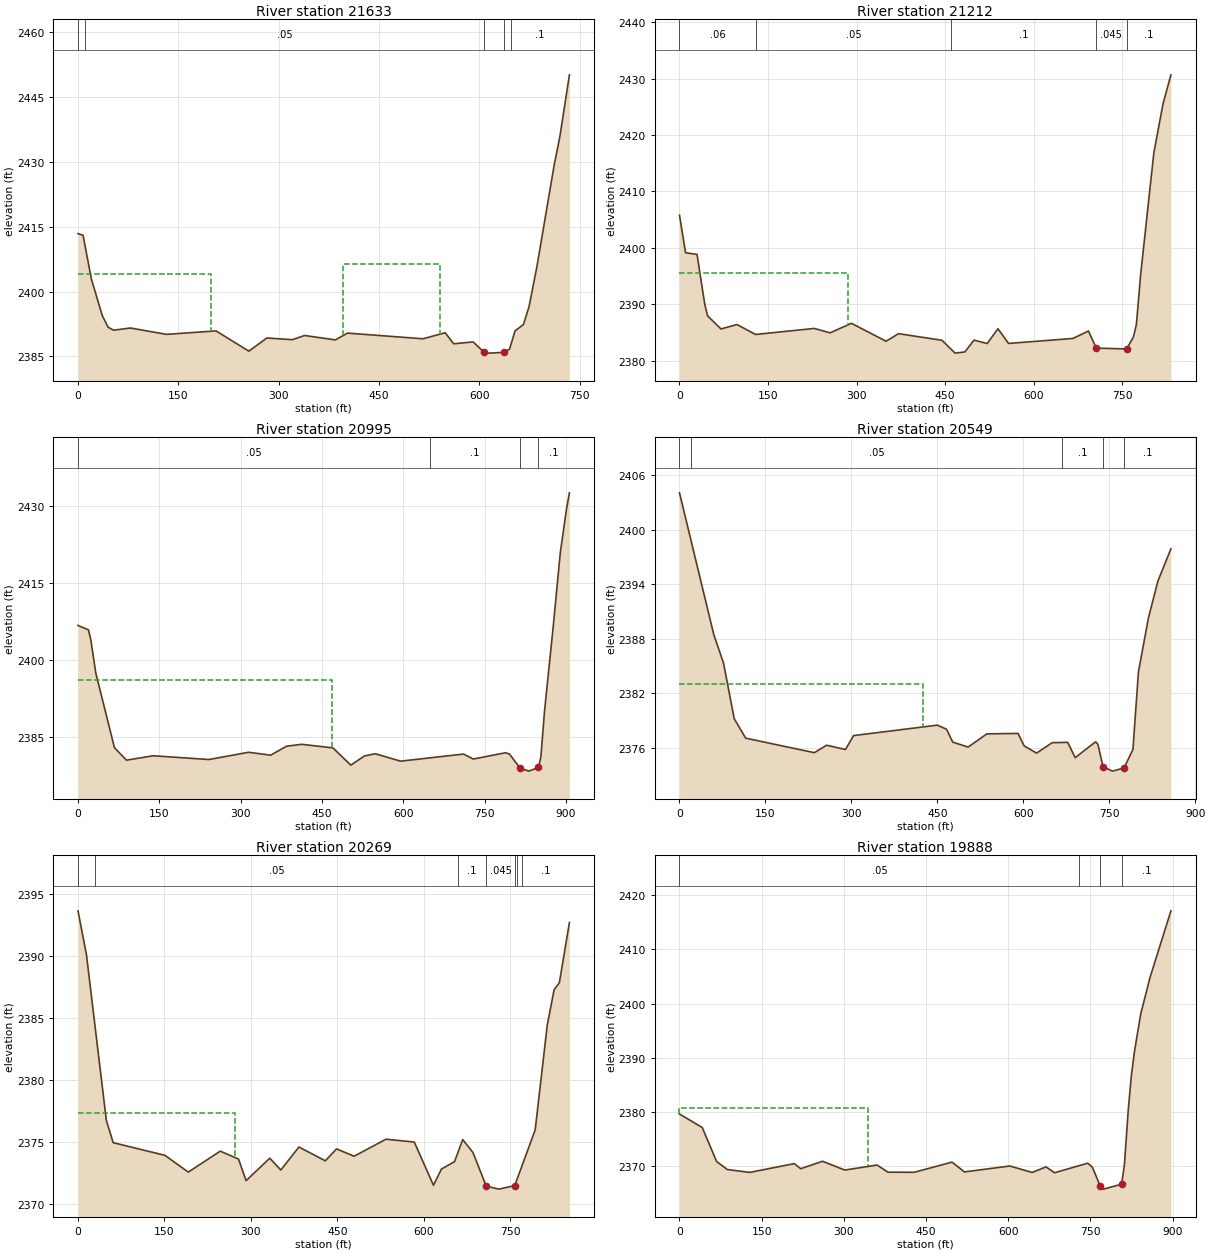
Type RM Length L Ch R = 1 ,21633   ,413.4,420.9,427.1
XS GIS Cut Line= 4
2253695.43615132491610.8836016062253510.44251395491557.772229347
2253333.89373809491454.9479134112253010.33796009491358.382283723
#Sta/Elev= 30
       0 2413.39     7.6 2413.01      20 2402.89    36.3 2394.43      45 2391.74
    53.3 2391.05    78.3 2391.56   132.4 2390.09   206.3 2390.89   255.3  2386.2
   282.3 2389.25   320.3 2388.86   338.6 2389.83   384.7 2388.81   402.7 2390.38
   515.5 2389.07   548.8 2390.46   561.4 2387.91   590.6 2388.34606.85522385.921
     615 2385.75636.7456 2385.93   644.9 2386.65   653.2 2390.91   665.7 2392.35
   674.1 2396.52   685.7 2405.66   711.6 2429.21     720 2435.69   734.4 2450.11
#Mann= 5 ,-1,0
       0     .06       0      10     .05       0606.8552    .045       0
636.7456     .05       0  646.78      .1       0
#XS Ineff= 2 ,-1
       0  198.072404.111  396.01  541.052406.439
Permanent Ineff=
       F       F
Bank Sta=606.8552,636.7456
XS Rating Curve= 0 ,0
Exp/Cntr(USF)=0,0
Exp/Cntr=0.3,0.1

Type RM Length L Ch R = 1 ,21212   ,219.2,217.1,215.9
XS GIS Cut Line= 2
2253898.49786656491332.7777481322253160.25038904  490947.7349263
#Sta/Elev= 30
       0 2405.78    10.3 2399.12    29.7 2398.82    42.9 2389.93    47.7 2387.91
    70.3  2385.6    97.4 2386.38   128.9 2384.62   228.2 2385.69   255.3 2384.91
   291.3  2386.6     350 2383.42   371.1 2384.76   444.7 2383.59   466.9 2381.31
   483.5 2381.52   498.9 2383.62   521.4 2383.01   539.5 2385.64   557.5 2383.03
   666.5 2383.91   692.9 2385.23   706.1  2382.2   757.5 2382.05     769 2384.16
   774.1 2386.39   781.2 2395.14   803.6 2416.79   819.2 2425.54   832.6 2430.68
#Mann= 5 ,-1,0
       0     .06       0     130     .05       0     460      .1       0
   706.1    .045       0   757.5      .1       0
#XS Ineff= 2 , 0
          285.63 2395.53
Permanent Ineff=
       F       F
Bank Sta=706.1,757.5
XS Rating Curve= 0 ,0
Exp/Cntr(USF)=0,0
Exp/Cntr=0.3,0.1

Type RM Length L Ch R = 1 ,20995   ,439,446.5,453.7
XS GIS Cut Line= 4
2254076.52034647491139.097122575 2253810.1440053490983.297296254
2253662.60864177490956.9516956242253261.08990903490758.758057995
#Sta/Elev= 30
       0 2406.72    19.2 2405.87    23.6 2403.98    32.8 2397.47    67.2 2382.94
    89.4  2380.5   138.5 2381.36   241.5 2380.63   314.7 2382.04   355.3 2381.47
   384.5 2383.21   412.2 2383.59   470.1 2382.89   503.1 2379.53   528.1 2381.32
   548.3 2381.75     595 2380.31     711 2381.69   728.9 2380.72   788.6 2381.95
   795.7 2381.68   815.5 2378.91   831.4 2378.37849.14842379.094   853.7 2381.25
   860.3 2390.07     876 2406.15   889.4 2420.88   900.8 2429.35   906.2 2432.52
#Mann= 4 ,-1,0
       0     .05       0  648.46      .1       0   815.5    .045       0
849.1484      .1       0
#XS Ineff= 2 , 0
          468.72 2396.19
Permanent Ineff=
       F       F
Bank Sta=815.5,849.1484
XS Rating Curve= 0 ,0
Exp/Cntr(USF)=0,0
Exp/Cntr=0.3,0.1

Type RM Length L Ch R = 1 ,20549   ,288.9,279.5,270
XS GIS Cut Line= 3
2254292.07191266490879.2028354452253911.69029863490734.116790265
2253579.20196404490429.953253609
#Sta/Elev= 30
       0 2404.07    59.8 2388.48    76.9 2385.32    95.5 2379.21   115.5 2377.07
   235.3 2375.47   256.8 2376.29   289.7 2375.82   303.8 2377.35     450  2378.5
   466.1 2378.05   476.9 2376.63   503.7 2376.09   536.6 2377.54   590.8 2377.59
   601.6 2376.21   623.3 2375.42   650.4 2376.57   677.5 2376.61   690.6 2374.92
   726.3 2376.67   730.2  2376.4739.31732373.914   755.7 2373.44775.8919 2373.79
   791.4 2375.83     801 2384.36   818.5 2390.32   834.9 2394.34   857.7 2397.91
#Mann= 5 ,-1,0
       0     .06       0      20     .05       0  667.11      .1       0
739.3173    .045       0775.8919      .1       0
#XS Ineff= 2 , 0
          425.25 2382.99
Permanent Ineff=
       F       F
Bank Sta=739.3173,775.8919
XS Rating Curve= 0 ,0
Exp/Cntr(USF)=0,0
Exp/Cntr=0.3,0.1

Type RM Length L Ch R = 1 ,20269   ,372.3,380.9,384.6
XS GIS Cut Line= 4
2254395.79688558490723.1968433122253968.30829496490393.846719298
2253872.03301364490304.0765245592253708.10483195490226.015485656
#Sta/Elev= 30
       0 2393.61    14.7 2390.08    49.2 2376.74    61.1 2374.94     151 2373.92
   191.4 2372.57   246.9 2374.26   278.6 2373.62   291.7 2371.88   332.8 2373.69
     352 2372.74   383.4 2374.59   429.3 2373.48   448.7 2374.44   479.2 2373.85
   534.5 2375.22   583.6 2374.99   616.9 2371.51   630.8 2372.82   653.4 2373.41
   667.6 2375.19   685.4 2374.15   708.42371.441   730.4  2371.2   757.9 2371.48
   793.4 2375.97   814.4 2384.42   826.2 2387.25   835.4 2387.83   852.8 2392.67
#Mann= 7 ,-1,0
       0     .06       0      30     .05       0  659.65      .1       0
   708.4    .045       0   757.9      .1       0  761.28     .05       0
  771.28      .1       0
#XS Ineff= 2 , 0
          272.43 2377.32
Permanent Ineff=
       F       F
Bank Sta=708.4,757.9
XS Rating Curve= 0 ,0
Exp/Cntr(USF)=0,0
Exp/Cntr=0.3,0.1

Type RM Length L Ch R = 1 ,19888   ,217.4,220.6,223.1
XS GIS Cut Line= 2
2254568.72482244490423.2113426262253865.56868783489866.397347707
#Sta/Elev= 30
       0 2379.61    41.5 2377.11    67.7 2370.84    87.3 2369.35   128.3 2368.82
   209.5 2370.44   221.1  2369.5     261 2370.88   301.7 2369.25   360.6 2370.18
   380.5 2368.86   428.5 2368.84   497.3 2370.72   520.1 2368.91   602.8    2370
   643.6 2368.81   669.1 2369.84   684.4 2368.75     745 2370.52   753.6 2369.78
   767.8 2366.31   773.5 2365.73   806.9 2366.63     812 2370.19   819.1 2380.47
   824.7  2386.7   830.4 2391.17   841.8  2398.1   858.9 2404.88   896.9 2417.14
#Mann= 4 ,-1,0
       0     .05       0     730      .1       0   767.8    .045       0
   806.9      .1       0
#XS Ineff= 2 , 0
          343.85 2380.78
Permanent Ineff=
       F       F
Bank Sta=767.8,806.9
XS Rating Curve= 0 ,0
Exp/Cntr(USF)=0,0
Exp/Cntr=0.3,0.1

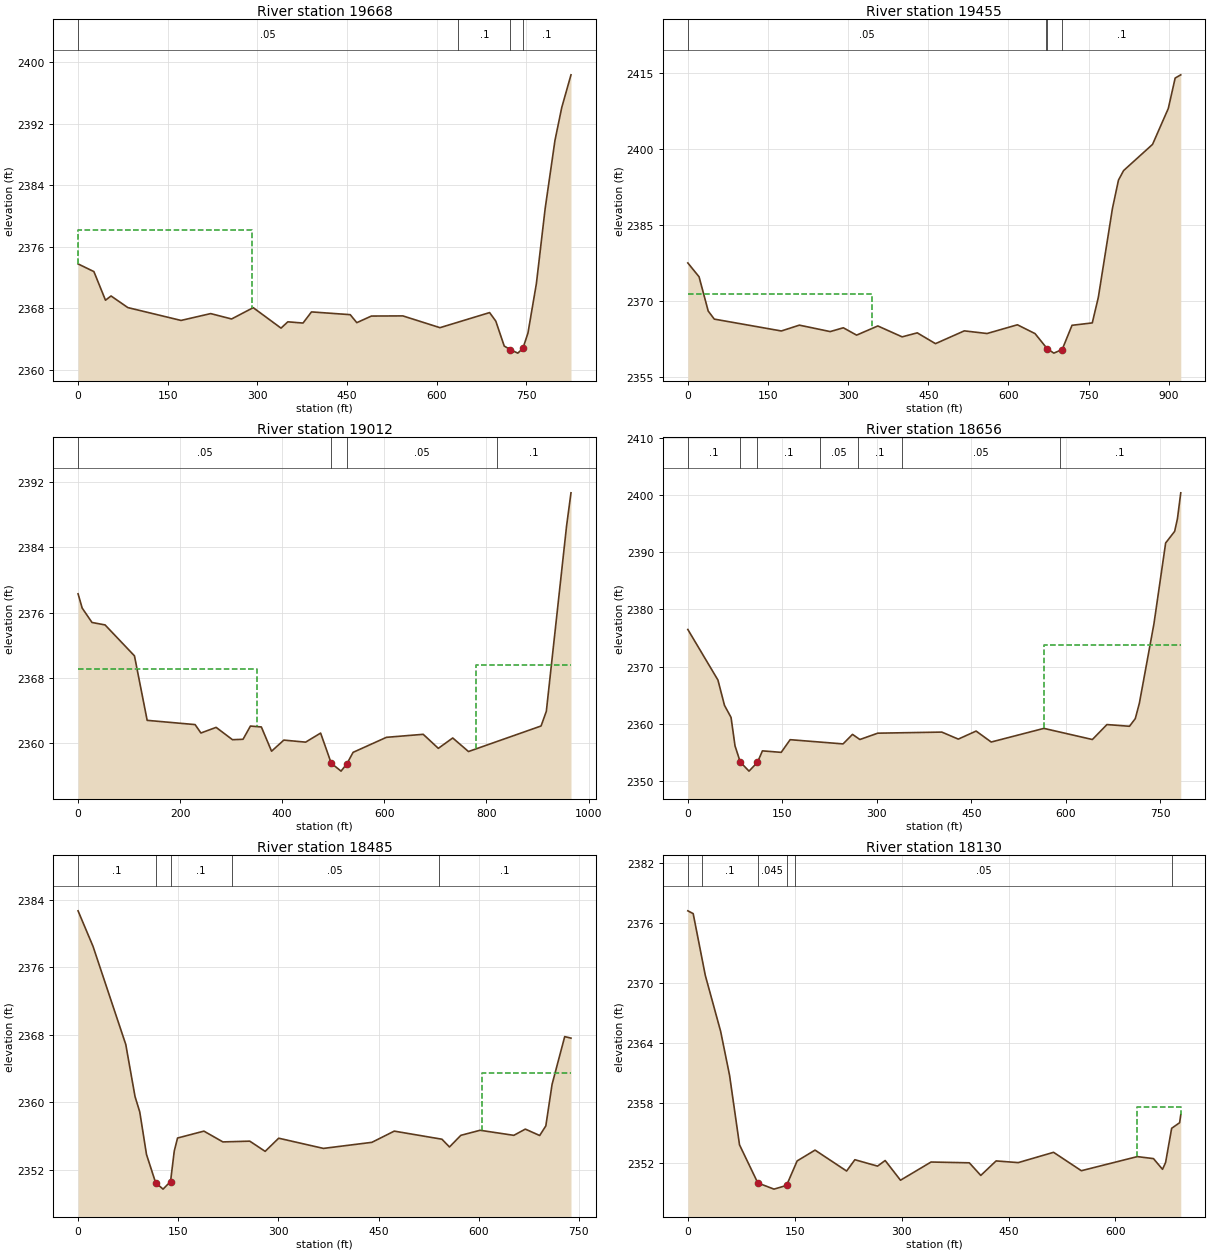
Type RM Length L Ch R = 1 ,19668   ,212.8,212.9,211.7
XS GIS Cut Line= 3
2254675.32981142490234.9619386412254431.04881441490085.941431864
2254040.04303861489715.497720245
#Sta/Elev= 30
       0 2373.79    26.5 2372.79    45.9 2369.07    55.2 2369.62    83.3 2368.11
   172.3 2366.44   221.9 2367.33   256.9 2366.63   293.1  2368.1   339.6 2365.44
     351 2366.26   376.4  2366.1   390.6 2367.55   455.4 2367.19   466.4 2366.15
   490.8 2367.01   543.4 2367.03   605.6  2365.5   688.6 2367.46     699 2366.35
   713.1 2363.11723.36412362.641   735.8 2362.19744.26422362.797   752.8  2364.8
   766.9 2371.23   781.6    2381     798 2389.85   809.3 2394.11   824.8 2398.37
#Mann= 4 ,-1,0
       0     .05       0  636.15      .1       0723.3641    .045       0
744.2642      .1       0
#XS Ineff= 2 , 0
           290.7 2378.14
Permanent Ineff=
       F       F
Bank Sta=723.3641,744.2642
XS Rating Curve= 0 ,0
Exp/Cntr(USF)=0,0
Exp/Cntr=0.3,0.1

Type RM Length L Ch R = 1 ,19455   ,425.4,442.8,462.6
XS GIS Cut Line= 3
2254766.86028192490150.0498286782254577.43123911489957.233427128
2254114.64992579  489497.7532623
#Sta/Elev= 30
       0 2377.48      21 2374.75    38.1    2368    49.5  2366.4     175 2364.06
   208.7 2365.21   266.4 2363.94     291 2364.69   315.8 2363.24   355.5 2365.05
     401  2362.9   429.3 2363.69   463.4 2361.56   517.3 2364.08   559.9 2363.56
   616.7 2365.28   649.7 2363.54   672.3 2360.59   684.8 2359.69   700.5  2360.4
   718.9 2365.18   756.8 2365.65   768.1 2370.67   794.5  2388.2   805.8 2393.81
   815.4  2395.7   869.6 2400.87   899.1 2407.96   911.9 2413.95   922.4 2414.59
#Mann= 4 ,-1,0
       0     .05       0   670.3      .1       0   672.3    .045       0
   700.5      .1       0
#XS Ineff= 2 , 0
          344.38 2371.33
Permanent Ineff=
       F       F
Bank Sta=672.3,700.5
XS Rating Curve= 0 ,0
Exp/Cntr(USF)=0,0
Exp/Cntr=0.3,0.1

Type RM Length L Ch R = 1 ,19012   ,374.2,356.1,333.7
XS GIS Cut Line= 4
2254925.25366507490050.4454473262254714.78340469489787.580316639
2254711.81138492 489522.981424012254434.02311285489287.228246957
#Sta/Elev= 30
       0 2378.31     8.1 2376.56    27.3  2374.8    52.9  2374.5   110.5 2370.71
   135.4 2362.81   229.3 2362.29   240.7 2361.26   270.5 2361.95   302.5 2360.44
   323.2 2360.49   337.7 2362.11   359.1    2362   379.1 2359.03   403.1 2360.39
   445.8 2360.14   475.2 2361.25     496 2357.56   515.2 2356.59   526.7 2357.49
   538.8 2358.89   604.1 2360.73   676.2  2361.1   705.8 2359.38     734 2360.65
   764.9 2358.99   907.1 2362.12   917.4 2363.92   957.1 2386.65   965.7 2390.68
#Mann= 4 ,-1,0
       0     .05       0     496    .045       0   526.7     .05       0
  821.36      .1       0
#XS Ineff= 2 , 0
          350.55 2369.11  780.54         2369.54
Permanent Ineff=
       F       F
Bank Sta=496,526.7
XS Rating Curve= 0 ,0
Exp/Cntr(USF)=0,0
Exp/Cntr=0.3,0.1

Type RM Length L Ch R = 1 ,18656   ,168.7,170.7,172.7
XS GIS Cut Line= 2
2255124.75081054489649.4156985512254525.89815219489145.744919671
#Sta/Elev= 30
       0 2376.49    47.8 2367.63    58.2 2363.19    68.6 2361.08    74.9  2356.1
    83.22353.272    97.1 2351.67   110.5 2353.21   118.4 2355.22   148.2 2354.96
   162.4 2357.18   246.4 2356.44   261.4 2358.11   273.1 2357.21   301.5 2358.32
   403.2 2358.51   429.3 2357.28   457.6 2358.69   481.6 2356.77   565.2 2359.16
   642.2 2357.21   665.3 2359.83   701.1 2359.53   710.3 2360.87   716.8 2363.58
   739.9 2377.47   758.5 2391.65   772.8 2393.69   777.2 2395.89   782.5 2400.44
#Mann= 7 ,-1,0
       0      .1       0    83.2    .045       0   110.5      .1       0
     210     .05       0     270      .1       0     340     .05       0
     590      .1       0
#XS Ineff= 2 , 0
                          565.64         2373.83
Permanent Ineff=
       F       F
Bank Sta=83.2,110.5
XS Rating Curve= 0 ,0
Exp/Cntr(USF)=0,0
Exp/Cntr=0.3,0.1

Type RM Length L Ch R = 1 ,18485   ,356,354.8,353.6
XS GIS Cut Line= 2
2255243.71392303489544.3687925882254728.40434312489015.599634098
#Sta/Elev= 30
       0 2382.69    22.3  2378.5    71.5 2366.83    85.3 2360.67    92.4 2358.84
   102.5 2353.79   116.2 2350.44   127.3 2349.68   138.5 2350.58   144.1  2354.2
     149 2355.74   188.5 2356.56   216.9 2355.28   257.2 2355.37   280.2 2354.16
   300.5 2355.72   367.5 2354.51   440.1 2355.23   473.6 2356.56     545  2355.6
   556.3 2354.68   573.3 2356.06   602.1 2356.66   652.7 2356.06   669.9  2356.8
   691.4 2356.04   700.6 2357.18     710 2362.12   728.9 2367.77   738.3 2367.59
#Mann= 5 ,-1,0
       0      .1       0   116.2    .045       0   138.5      .1       0
     230     .05       0     540      .1       0
#XS Ineff= 2 , 0
                          604.57         2363.44
Permanent Ineff=
       F       F
Bank Sta=116.2,138.5
XS Rating Curve= 0 ,0
Exp/Cntr(USF)=0,0
Exp/Cntr=0.3,0.1

Type RM Length L Ch R = 1 ,18130   ,399.2,401.1,402.4
XS GIS Cut Line= 2
2255474.44955583489265.5632362932254959.13997592488804.091970702
#Sta/Elev= 30
       0  2377.2     7.5 2376.92    24.5 2370.75      46 2365.16    58.5 2360.78
    72.5 2353.81    98.2    2350   120.9 2349.38   138.5 2349.75   153.4  2352.2
   178.5 2353.28   222.8 2351.19   234.4 2352.32   266.2 2351.68   276.9 2352.24
   298.4 2350.27   341.3 2352.09     395 2352.01   411.1 2350.75   432.6  2352.2
   463.6 2352.03   513.2 2353.06   552.2 2351.22   630.7 2352.63   653.4 2352.43
   666.1 2351.36   670.4 2352.04   678.9 2355.46   690.1 2356.02   691.7 2356.82
#Mann= 6 ,-1,0
       0     .06       0      20      .1       0    98.2    .045       0
   138.5      .1       0     150     .05       0     680      .1       0
#XS Ineff= 2 , 0
                          629.79         2357.54
Permanent Ineff=
       F       F
Bank Sta=98.2,138.5
XS Rating Curve= 0 ,0
Exp/Cntr(USF)=0,0
Exp/Cntr=0.3,0.1

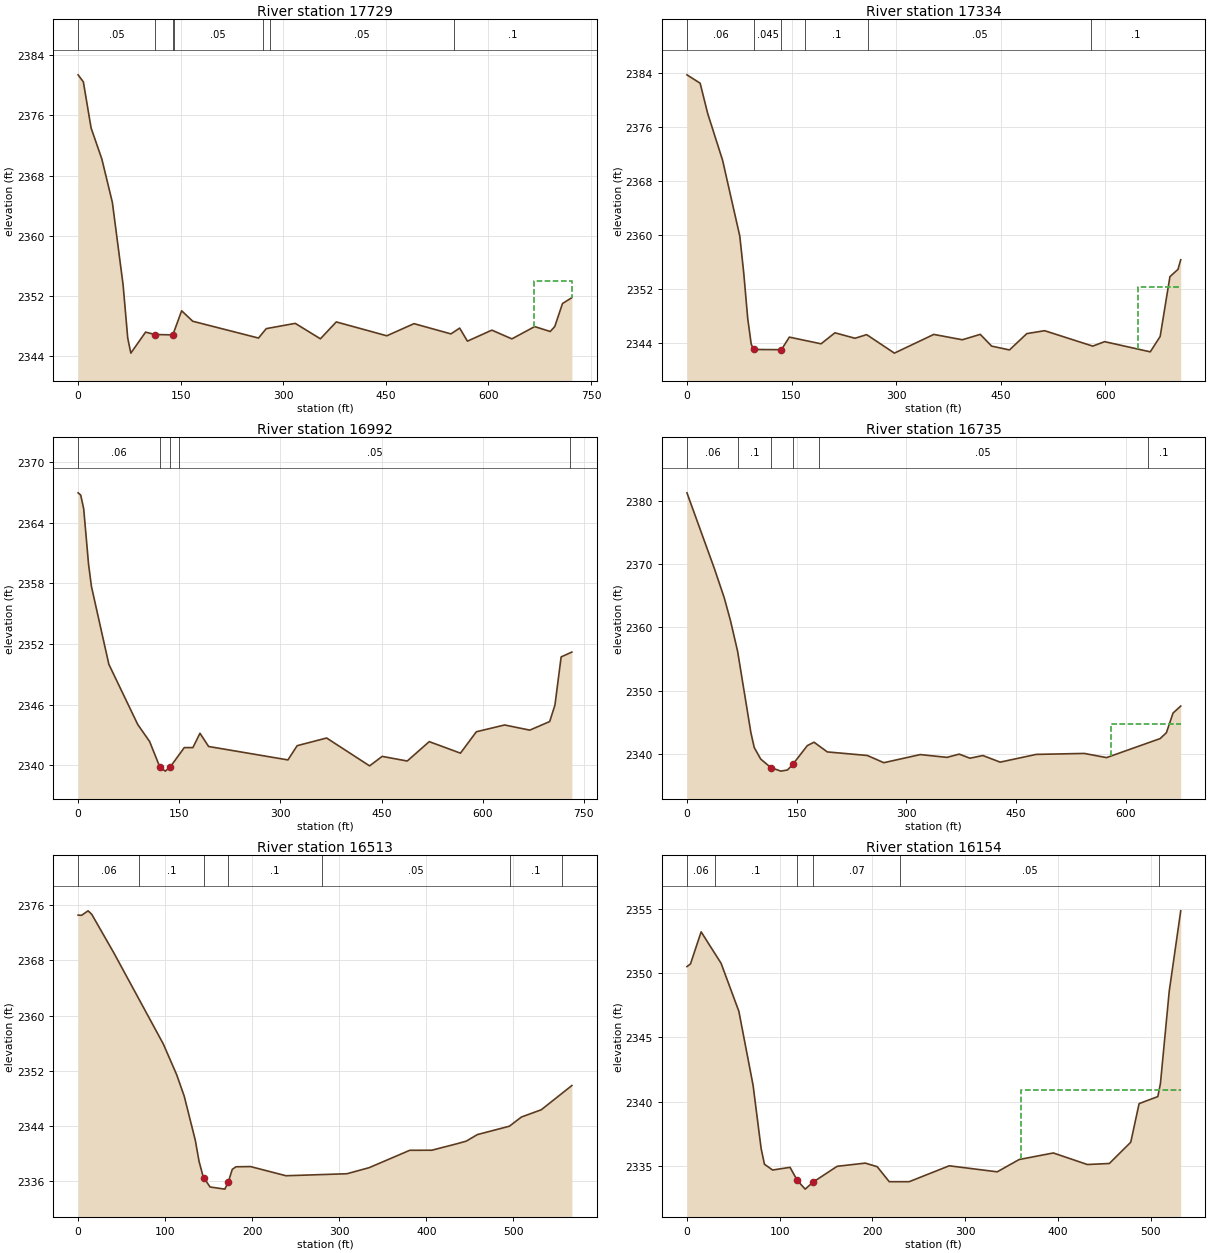
Type RM Length L Ch R = 1 ,17729   ,397.8,394.9,393.4
XS GIS Cut Line= 2
2255745.56392436488984.8348830582255237.94553221488471.448100088
#Sta/Elev= 30
       0 2381.36     7.7 2380.42      19 2374.31    34.7  2370.2    50.1 2364.44
    65.8 2353.49    72.6 2346.42    77.1 2344.44    98.7 2347.23     112 2346.91
   138.5 2346.86   151.4 2350.06   167.6 2348.67   263.8 2346.44   275.1 2347.69
   317.5 2348.39   354.3 2346.34   377.5 2348.58   451.4 2346.74   491.2 2348.35
   545.2 2346.99   557.9 2347.76   569.3 2346.03     605 2347.49   634.3 2346.33
   667.6 2347.96   690.4 2347.31     697 2347.97   708.3 2351.02     722  2351.8
#Mann= 7 ,-1,0
       0     .05       0     112    .045       0   138.5      .1       0
     140     .05       0     270      .1       0     280     .05       0
     550      .1       0
#XS Ineff= 2 , 0
                          666.53         2354.04
Permanent Ineff=
       F       F
Bank Sta=112,138.5
XS Rating Curve= 0 ,0
Exp/Cntr(USF)=0,0
Exp/Cntr=0.3,0.1

Type RM Length L Ch R = 1 ,17334   ,345.5,342.7,339.9
XS GIS Cut Line= 2
2255983.99074492488659.8822002042255432.14802315488215.716107072
#Sta/Elev= 30
       0 2383.68    18.9 2382.44    29.8 2377.94    51.1 2371.04    75.8  2359.8
    81.4 2354.41    87.2 2347.58    92.2  2343.8    95.7 2343.01   135.5 2342.98
   146.9 2344.84   192.4 2343.85   212.3 2345.48   241.1 2344.67   257.8 2345.21
   297.6 2342.47   354.1 2345.24   395.1 2344.45   420.8 2345.25   437.1 2343.51
   462.7 2342.94   487.6 2345.36   513.2 2345.79   582.2 2343.51   599.2 2344.17
   664.7 2342.66   678.9 2344.94   692.9 2353.79   704.5 2354.88   708.4  2356.3
#Mann= 6 ,-1,0
       0     .06       0    95.7    .045       0   135.5     .05       0
     170      .1       0     260     .05       0     580      .1       0
#XS Ineff= 2 , 0
                          647.47         2352.32
Permanent Ineff=
       F       F
Bank Sta=95.7,135.5
XS Rating Curve= 0 ,0
Exp/Cntr(USF)=0,0
Exp/Cntr=0.3,0.1

Type RM Length L Ch R = 1 ,16992   ,257.2,257,257
XS GIS Cut Line= 2
 2256199.3440022488375.3082530892255570.58940283488000.362849796
#Sta/Elev= 30
       0 2366.97     3.9 2366.74     8.3 2365.39    15.5  2359.9    19.8 2357.69
    45.6 2349.99    88.5 2344.02     106 2342.35   121.3  2339.8   129.3 2339.41
   136.9 2339.85   157.4 2341.74   170.2 2341.74   180.7 2343.16   193.5 2341.85
   311.1 2340.52   324.8 2341.93   368.5 2342.69   432.2 2339.93   450.8 2340.87
     488 2340.41   520.6 2342.33   566.9 2341.19   590.5 2343.31   632.4 2343.98
   669.7 2343.47   699.2 2344.32     707 2345.95   716.2 2350.72   732.1  2351.2
#Mann= 5 ,-1,0
       0     .06       0   121.3    .045       0   136.9     .06       0
     150     .05       0     730     .06       0
Bank Sta=121.3,136.9
XS Rating Curve= 0 ,0
Exp/Cntr(USF)=0,0
Exp/Cntr=0.3,0.1

Type RM Length L Ch R = 1 ,16735   ,224.8,221.3,217
XS GIS Cut Line= 2
2256305.09783389488136.8814325342255710.95357944487815.774343559
#Sta/Elev= 30
       0 2381.22    37.4 2369.31    51.1 2364.63    59.5 2361.08    69.3 2356.22
    87.4 2343.43      92 2341.06   100.8 2339.24   114.7 2337.89   128.4 2337.33
   137.5 2337.51   144.72338.386   164.7 2341.36   173.8 2341.89     192 2340.36
   246.6  2339.8   269.3 2338.66   319.1 2339.94   355.7  2339.5   372.4 2340.01
   387.1 2339.37   404.8 2339.79   428.4 2338.75   477.9 2339.97   543.6 2340.12
   573.9 2339.46   647.2 2342.46   655.8 2343.39   664.9 2346.49   675.4 2347.59
#Mann= 6 ,-1,0
       0     .06       0      70      .1       0   114.7    .045       0
   144.7      .1       0     180     .05       0     630      .1       0
#XS Ineff= 2 , 0
                          580.23         2344.78
Permanent Ineff=
       F       F
Bank Sta=114.7,144.7
XS Rating Curve= 0 ,0
Exp/Cntr(USF)=0,0
Exp/Cntr=0.3,0.1

Type RM Length L Ch R = 1 ,16513   ,358,359.4,362
XS GIS Cut Line= 3
2256407.00607171487923.4509721972256024.36948066 487786.93238946
2255945.53480612487646.568212842
#Sta/Elev= 30
       0 2374.57       4 2374.54    11.5 2375.19    15.7 2374.68    41.2 2369.06
    97.9 2355.88   113.2 2351.44   121.9 2348.32   134.7 2341.89   138.9 2338.89
   143.2 2336.86   144.9 2336.39   151.6 2335.15   168.6 2334.84   172.6 2335.91
   177.1 2337.71   181.4 2338.08   198.1 2338.11   238.8 2336.78   308.8 2337.07
   334.3 2337.95     381 2340.47   406.3 2340.48   435.8 2341.44   445.9  2341.8
   458.7 2342.75   495.4 2343.96   509.2 2345.29   532.1 2346.35   567.2 2349.86
#Mann= 7 ,-1,0
       0     .06       0      70      .1       0   144.9    .045       0
   172.6      .1       0     280     .05       0  496.26      .1       0
  556.26     .06       0
Bank Sta=144.9,172.6
XS Rating Curve= 0 ,0
Exp/Cntr(USF)=0,0
Exp/Cntr=0.3,0.1

Type RM Length L Ch R = 1 ,16154   ,77.8,76.3,74.2
XS GIS Cut Line= 3
2256554.31336404  487619.92896372256184.26111363 487469.71608656
2256069.46033005487402.031749932
#Sta/Elev= 30
       0 2350.53     3.8 2350.74    15.3 2353.24    36.8 2350.79      56 2347.04
    71.3 2341.28      80 2336.34    83.6 2335.11    92.4 2334.66   111.2 2334.87
   118.9 2333.86   127.5 2333.17   136.1 2333.72     162 2334.95   192.3  2335.2
   205.2 2334.92   218.2 2333.75   239.7 2333.75   282.9 2334.99   334.7 2334.52
   358.3 2335.48   395.2 2335.99   431.9 2335.09   455.6 2335.17   478.7 2336.83
   487.7 2339.84   507.9 2340.39   510.7  2341.4   520.2 2348.61   532.6 2354.88
#Mann= 6 ,-1,0
       0     .06       0      30      .1       0   118.9    .045       0
   136.1     .07       0     230     .05       0  509.38     .06       0
#XS Ineff= 2 , 0
                          360.48          2340.9
Permanent Ineff=
       F       F
Bank Sta=118.9,136.1
XS Rating Curve= 0 ,0
Exp/Cntr(USF)=0,0
Exp/Cntr=0.3,0.1

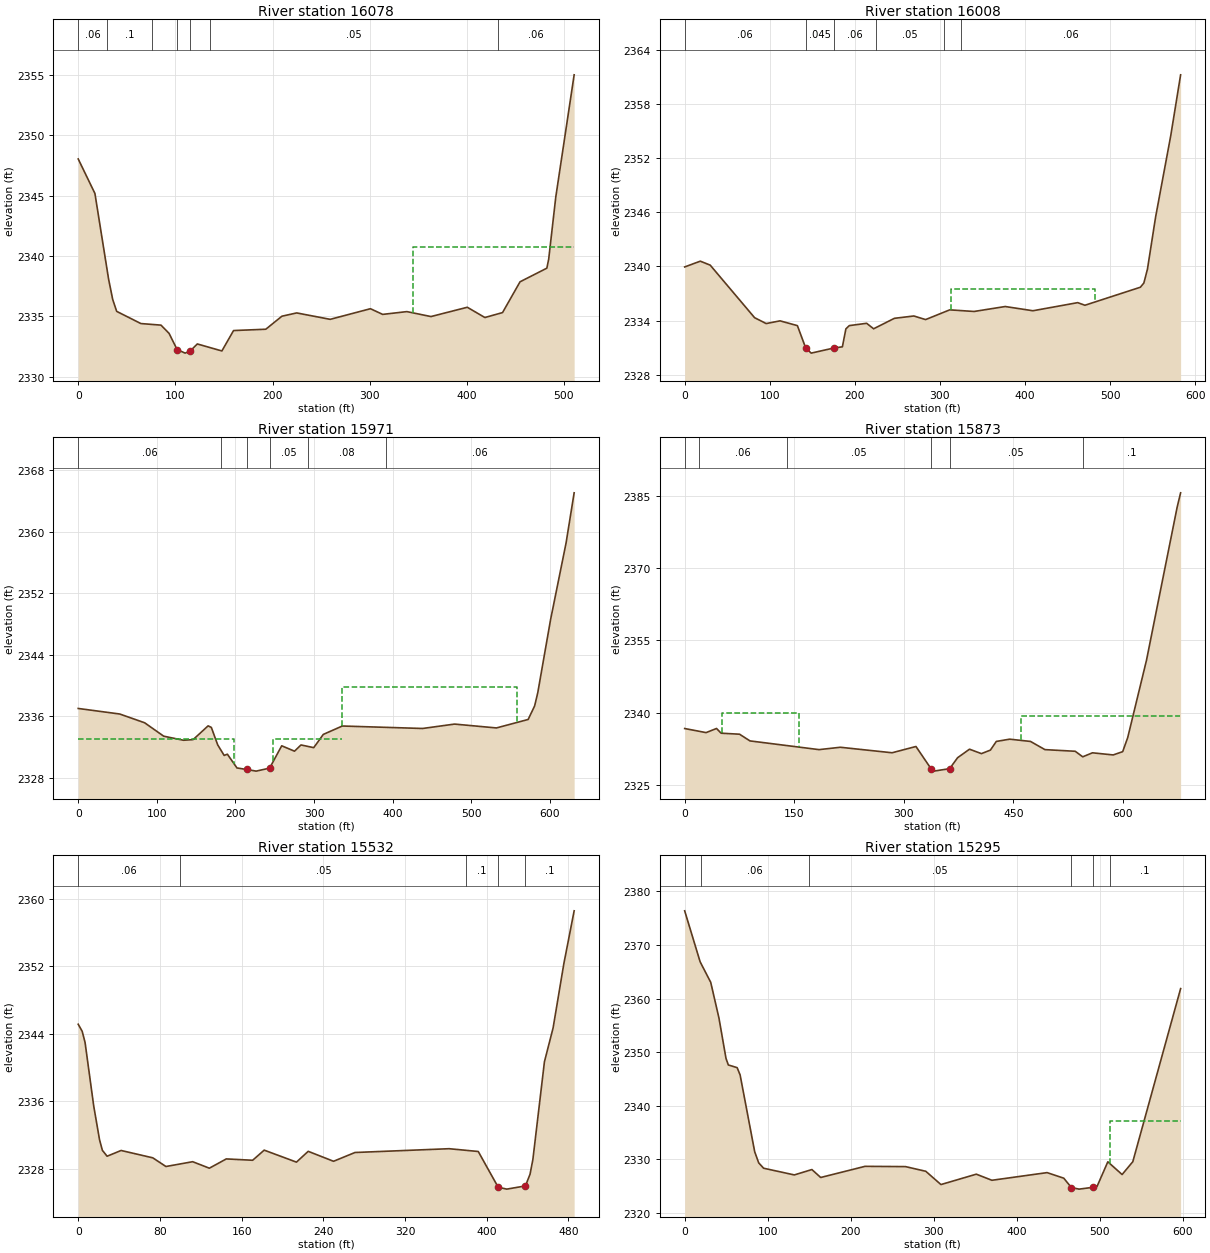
Type RM Length L Ch R = 1 ,16078   ,77.7,69.6,68.1
BEGIN DESCRIPTION:
xs 4
END DESCRIPTION:
XS GIS Cut Line= 4
2256563.66033762487549.9143471592256540.15771566487523.346165816
2256186.59653318487426.2701186022256091.56419222487374.155609044
#Sta/Elev= 30
       0 2348.03    17.2 2345.17    31.3 2338.06    35.5 2336.39    39.6  2335.4
    64.5 2334.39    85.2 2334.26    93.5 2333.58   101.8 2332.24   110.1 2331.94
   115.3 2332.12   122.6  2332.7   147.9 2332.12   159.9 2333.81   193.1 2333.92
   209.7    2335   224.9 2335.27   259.4 2334.74   300.8 2335.62   313.4 2335.15
   338.3 2335.38   363.1 2334.97   400.5 2335.74   418.6 2334.89   436.8  2335.3
   454.8 2337.85   482.4 2338.98   484.3 2339.73   491.6 2344.88   510.5    2355
#Mann= 7 ,-1,0
       0     .06       0      30      .1       0   75.47     .06       0
   101.8    .045       0   115.3     .06       0  135.47     .05       0
  432.12     .06       0
#XS Ineff= 2 , 0
                          344.99         2340.73
Permanent Ineff=
       F       F
Bank Sta=101.8,115.3
XS Rating Curve= 0 ,0
Exp/Cntr(USF)=0,0
Exp/Cntr=0.5,0.3

Type RM Length L Ch R = 1 ,16008   ,37.9,37,37.1
XS GIS Cut Line= 3
2256652.37034363 487499.521355462256569.10823685487454.105660857
2256089.72034937487362.012724578
#Sta/Elev= 30
       0 2339.95    18.4 2340.59      30 2340.15    82.2 2334.32    95.8 2333.67
   112.1 2333.97   132.5 2333.44   142.2 2330.98   148.7 2330.39     175 2330.95
   185.4 2331.09   189.5 2333.08   193.5 2333.44   213.9  2333.7   222.1 2333.09
   246.5 2334.25   269.4 2334.51   283.2 2334.11   311.6 2335.19   340.2 2335.01
   376.8 2335.56   409.4 2335.09     462 2335.99   470.5  2335.7   535.7  2337.7
   539.8 2338.17     544  2339.7   553.6 2345.49   571.4 2354.51     583 2361.26
#Mann= 6 ,-1,0
       0     .06       0   142.2    .045       0     175     .06       0
  224.84     .05       0  304.84     .08       0  324.84     .06       0
#XS Ineff= 3 ,-1
       0     130  2333.4     200  312.81  2333.4  312.81  482.62 2337.45
Permanent Ineff=
       F       F       F
Bank Sta=142.2,175
XS Rating Curve= 0 ,0
Exp/Cntr(USF)=0,0
Exp/Cntr=0.5,0.3

Type RM Length L Ch R = 1 ,15971   ,99,98.4,100.1
XS GIS Cut Line= 3
2256710.14538375487496.5703943872256600.83866882487422.566984049
2256110.65572304487330.600202477
#Sta/Elev= 30
       0 2337.02    52.8  2336.3    84.5 2335.16   108.7 2333.42   133.8 2332.89
   146.1 2332.97   165.2 2334.76   169.3 2334.56   177.4 2332.29   185.6 2330.92
   189.7 2331.08   201.9 2329.29   214.1  2329.1   226.3 2328.88   243.4 2329.27
   258.8 2332.17   275.1 2331.47   283.3 2332.28   299.5 2331.93   311.7 2333.65
   335.9 2334.74   437.9 2334.42   478.6 2334.99   531.9 2334.49   572.2 2335.59
   580.4 2337.34   584.4 2339.05   600.7 2348.55   620.4  2358.5   630.7 2365.03
#Mann= 6 ,-1,0
       0     .06       0     182     .05       0   214.1    .045       0
   243.4     .05       0     292     .08       0     392     .06       0
#XS Ineff= 3 ,-1
       0     198    2333     248  335.75    2333  335.75  558.19 2339.84
Permanent Ineff=
       F       F       F
Bank Sta=214.1,243.4
XS Rating Curve= 0 ,0
Exp/Cntr(USF)=0,0
Exp/Cntr=0.5,0.3

Type RM Length L Ch R = 1 ,15873   ,327.7,340.1,354.7
XS GIS Cut Line= 4
2256796.64514005487521.5709146992256662.00847559487336.241862449
2256450.29643703487294.5438728892256301.88330162487113.559844295
#Sta/Elev= 30
       0  2336.7    29.3 2335.85    43.6 2336.71    49.9 2335.73    75.1 2335.52
    89.4 2334.13   183.9 2332.32   213.1 2332.81   283.9 2331.67   316.6 2332.97
337.09032328.394     341 2327.86   362.7 2328.37   373.6 2330.64   389.9 2332.41
   406.2 2331.49   418.5 2332.22   426.6 2334.02   444.9 2334.49   473.4 2334.02
   493.2 2332.32   534.6 2331.98   544.9 2330.83   558.2 2331.66   586.6 2331.22
   599.6  2331.9   606.5 2334.83   632.1 2350.81   674.2 2382.66   678.9  2385.6
#Mann= 6 ,-1,0
       0      .1       0      20     .06       0     140     .05       0
337.0903    .045       0   362.7     .05       0  544.85      .1       0
#XS Ineff= 2 ,-1
   51.44  156.412339.985  460.47   677.6 2339.34
Permanent Ineff=
       F       F
Bank Sta=337.0903,362.7
XS Rating Curve= 0 ,0
Exp/Cntr(USF)=0,0
Exp/Cntr=0.3,0.1

Type RM Length L Ch R = 1 ,15532   ,227.3,237.2,246.8
XS GIS Cut Line= 2
 2256920.3923015487282.5014990592256572.96223779486943.246260372
#Sta/Elev= 30
       0 2345.13     3.9 2344.29     6.7 2342.98    15.2 2335.43    20.9 2331.43
    23.7 2330.18    28.3 2329.49      42 2330.17      73  2329.3    85.9 2328.27
   112.1 2328.84   128.4 2328.07     145 2329.17   170.8 2329.01   182.1 2330.21
   213.7 2328.79   225.2 2330.07     250 2328.89     271 2329.93   363.2 2330.38
   391.7 2330.05   411.2 2325.82   419.6 2325.59   437.9 2325.97   442.4 2327.35
   445.2 2329.11   456.5 2340.68     465  2344.7   475.5  2352.3   485.6 2358.57
#Mann= 5 ,-1,0
       0     .06       0     100     .05       0     380      .1       0
   411.2    .045       0   437.9      .1       0
Bank Sta=411.2,437.9
XS Rating Curve= 0 ,0
Exp/Cntr(USF)=0,0
Exp/Cntr=0.3,0.1

Type RM Length L Ch R = 1 ,15295   ,475.6,466.5,463.2
XS GIS Cut Line= 3
2257098.70344758487228.871854875 2256834.9702629486925.382079326
2256762.93708481486743.629170038
#Sta/Elev= 30
       0 2376.38    18.6 2366.88    31.4 2363.04    41.3 2356.39    49.8 2348.85
    52.6 2347.63    63.2 2347.13    66.8 2345.77    84.4 2331.42    89.2 2329.37
    95.1 2328.37   132.1 2327.12   153.3 2328.12   163.9 2326.64   217.3 2328.72
   266.1 2328.67   290.5  2327.8   308.8 2325.32   351.4 2327.26   370.2 2326.12
   436.7 2327.55   456.8 2326.51     466 2324.76   475.3 2324.47   492.6 2324.82
   496.9 2324.97   509.9 2329.57   527.1 2327.19     540 2329.59   597.6 2361.87
#Mann= 6 ,-1,0
       0      .1       0      20     .06       0     150     .05       0
     466    .045       0   492.6     .05       0  512.07      .1       0
#XS Ineff= 2 , 0
                          512.41         2337.13
Permanent Ineff=
       F       F
Bank Sta=466,492.6
XS Rating Curve= 0 ,0
Exp/Cntr(USF)=0,0
Exp/Cntr=0.3,0.1