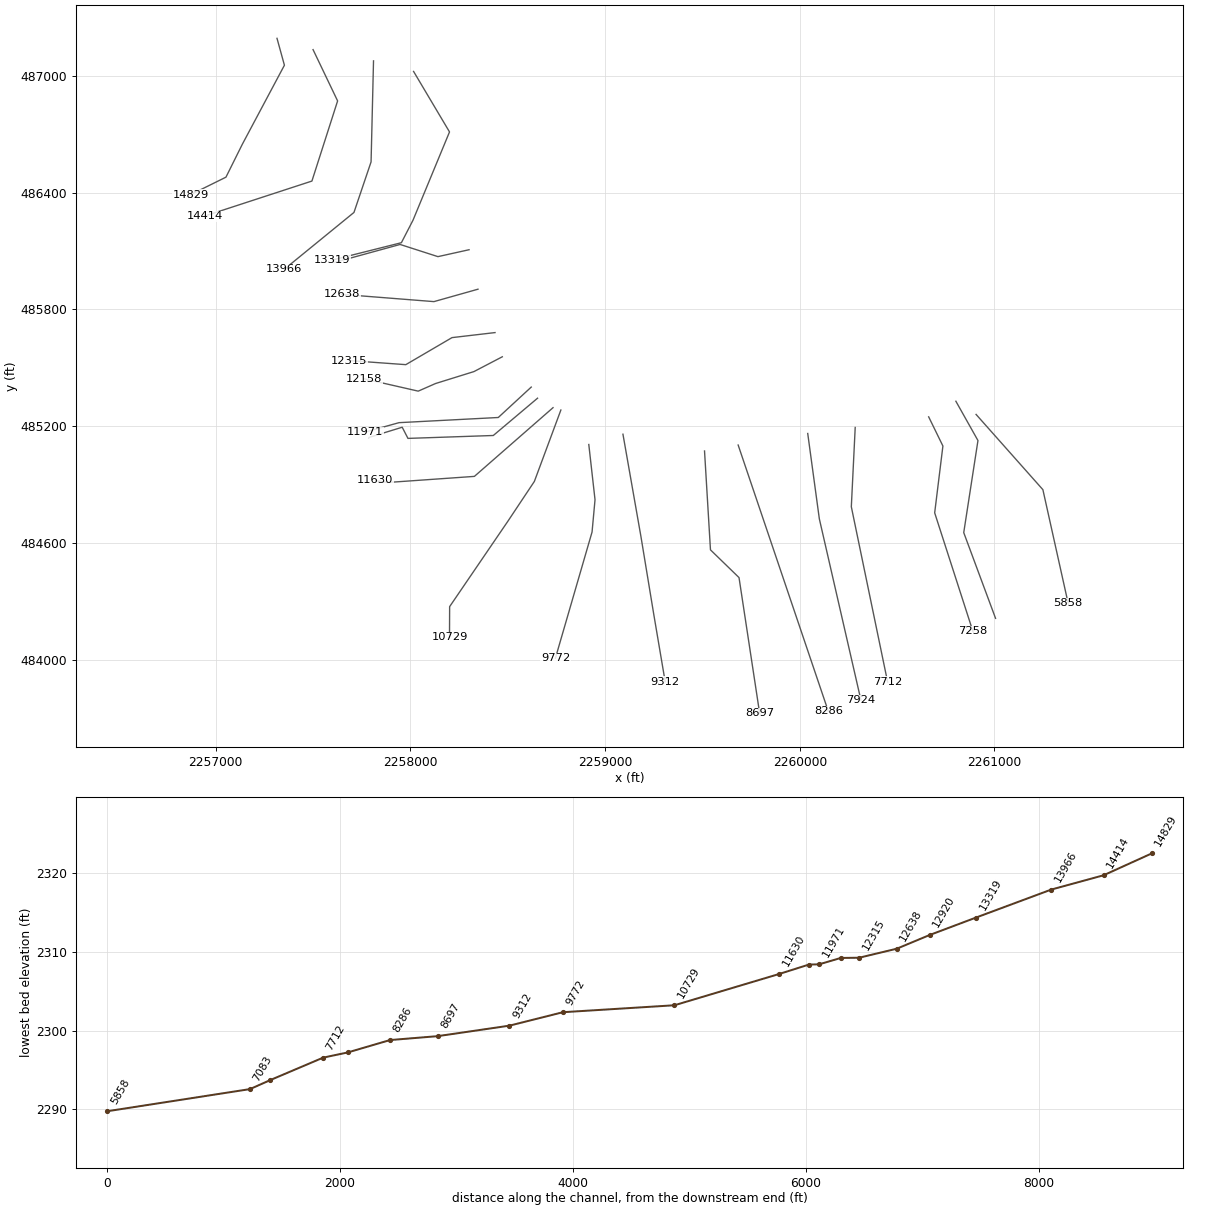
HEC-RAS study CLOVERCK.prj: CLOVERCK

--- CLOVERCK.g01 (geometry) --- (continued)

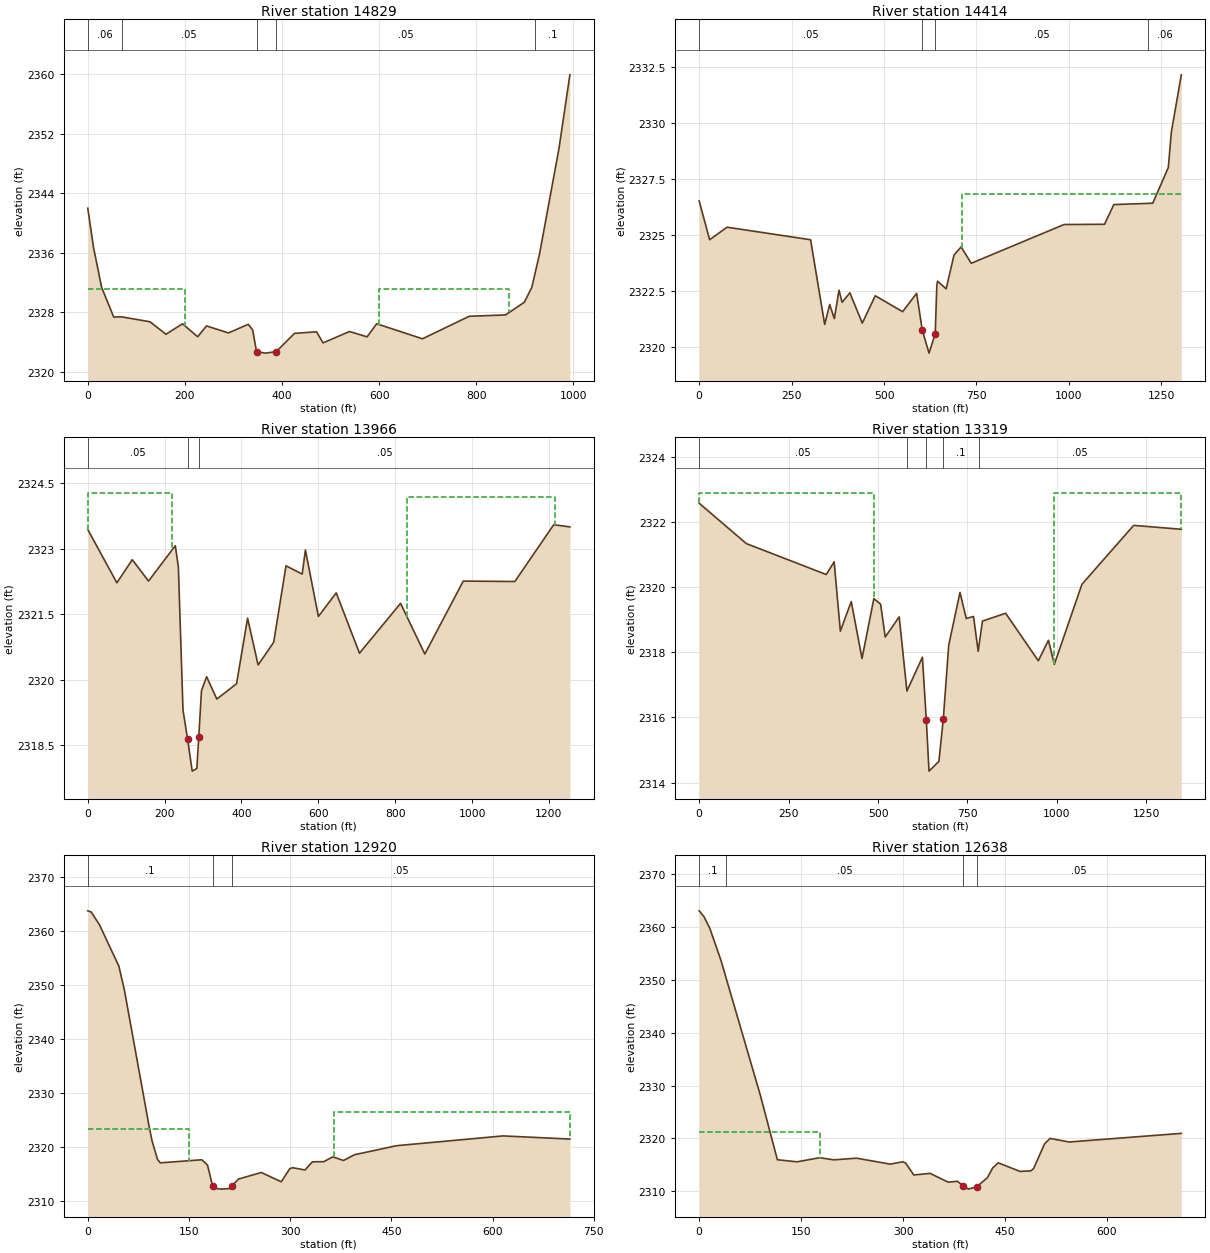
Type RM Length L Ch R = 1 ,14829   ,413,414.4,421.2
XS GIS Cut Line= 5
2257314.44418334487192.6613274852257352.51291356487054.490528065
2257136.23867928486648.4166873722257052.19490757486479.455030092
2256872.08048663 486390.40937393
#Sta/Elev= 30
       0    2342    11.9 2336.71    28.5 2331.36    53.4 2327.36      70 2327.38
   128.1 2326.72   161.1 2325.04   195.1 2326.45   226.4  2324.7   244.5 2326.16
   289.8 2325.22   330.6 2326.38   339.7  2325.6   347.6  2322.7   366.3  2322.5
   388.1  2322.7   425.8 2325.16   471.1 2325.37   484.7 2323.88   539.1 2325.41
   575.3 2324.69     595 2326.45   689.4 2324.43   785.7 2327.46   860.4 2327.64
   899.2 2329.35   914.6 2331.35   930.5 2335.85   970.6 2350.07     993 2359.95
#Mann= 5 ,-1,0
       0     .06       0      70     .05       0   347.6    .045       0
   388.1     .05       0  922.11      .1       0
#XS Ineff= 2 ,-1
       0   199.6 2331.12  600.79     868 2331.17
Permanent Ineff=
       F       F
Bank Sta=347.6,388.1
XS Rating Curve= 0 ,0
Exp/Cntr(USF)=0,0
Exp/Cntr=0.3,0.1

Type RM Length L Ch R = 1 ,14414   ,432.9,448,453.6
XS GIS Cut Line= 4
2257499.64041104487134.6641569342257625.77240589 486871.12265648
2257493.80382113486459.4397345412256942.66861962486279.586309076
#Sta/Elev= 30
       0 2326.51    28.3 2324.78    75.4 2325.34   301.3 2324.78   339.5    2321
     353 2321.89   365.6 2321.26   378.2 2322.53   386.6 2321.99   407.6 2322.41
   441.2 2321.06   476.3 2322.28   550.4 2321.57   588.2 2322.39   603.42320.754
   621.8 2319.72   638.5 2320.58   642.9 2322.76   644.9 2322.93   668.1 2322.59
   689.4  2324.1   708.5 2324.46     736 2323.73   987.1 2325.46  1096.5 2325.47
  1121.7 2326.35  1226.9 2326.41    1269    2328  1277.4  2329.6  1304.2 2332.14
#Mann= 4 ,-1,0
       0     .05       0   603.4    .045       0   638.5     .05       0
 1214.49     .06       0
#XS Ineff= 2 , 0
                          710.43         2326.82
Permanent Ineff=
       F       F
Bank Sta=603.4,638.5
XS Rating Curve= 0 ,0
Exp/Cntr(USF)=0,0
Exp/Cntr=0.3,0.1

Type RM Length L Ch R = 1 ,13966   ,636,647.3,633
XS GIS Cut Line= 4
2257810.26071479487076.9433407452257797.69944037486558.021999417
2257709.77801651 486298.190200422257352.32756942486006.617763261
#Sta/Elev= 30
       0 2323.44    75.8 2322.22   115.8 2322.75   158.1 2322.26   227.8 2323.07
   235.8 2322.58   247.8 2319.31   259.8 2318.64   271.8 2317.91   283.8 2317.97
   288.8 2318.68   295.9 2319.75   309.3 2320.07   335.9 2319.56   387.2 2319.91
   415.9 2321.41   443.3 2320.34   483.9 2320.86   515.9 2322.61     558 2322.42
   566.4 2322.97   600.2 2321.45   646.6 2321.99   707.1 2320.61     814 2321.75
   877.2 2320.59   977.2 2322.26  1111.4 2322.25  1212.6 2323.55  1254.7  2323.5
#Mann= 3 ,-1,0
       0     .05       0   259.8    .045       0   288.8     .05       0
#XS Ineff= 2 ,-1
       0  218.07 2324.28  831.42 1216.482324.182
Permanent Ineff=
       F       F
Bank Sta=259.8,288.8
XS Rating Curve= 0 ,0
Exp/Cntr(USF)=0,0
Exp/Cntr=0.3,0.1

Type RM Length L Ch R = 1 ,13319   ,445.6,398.9,350.1
XS GIS Cut Line= 5
2258016.08263133  487022.59595792258200.65200751486711.839664156
2258013.16761028486258.4757102362257953.46392208486142.788219386
2257599.00105758486053.824799681
#Sta/Elev= 30
       0 2322.58   131.9 2321.34   355.2 2320.39   377.3 2320.78   394.6 2318.65
   425.1 2319.56   455.2 2317.81   488.3 2319.65   507.2 2319.48     520 2318.47
   559.1 2319.09   580.7 2316.81     624 2317.85   634.8 2315.93   642.5 2314.35
   670.1 2314.65  682.492315.966   697.6 2318.22     729 2319.84   746.6 2319.04
   766.9  2319.1   779.9 2318.03   791.8 2318.96   856.7  2319.2     948 2317.74
   976.3 2318.37   992.8 2317.63  1069.9 2320.09  1214.5  2321.9  1347.7 2321.78
#Mann= 5 ,-1,0
       0     .05       0  581.44      .1       0   634.8    .045       0
  682.49      .1       0  781.44     .05       0
#XS Ineff= 2 , 0
          487.98  2322.9  993.02         2322.88
Permanent Ineff=
       F       F
Bank Sta=634.8,682.49
XS Rating Curve= 0 ,0
Exp/Cntr(USF)=0,0
Exp/Cntr=0.3,0.1

Type RM Length L Ch R = 1 ,12920   ,279.8,282.4,286.2
XS GIS Cut Line= 4
2258301.13378174486106.7085190782258141.19486358486071.224179607
 2257946.7160794486133.7975995022257612.51713169486042.099204613
#Sta/Elev= 30
       0  2363.7     5.1 2363.48    17.4  2361.1    46.1 2353.45    54.2 2349.08
    91.1 2323.65    95.2 2321.12   103.4 2317.63   107.5    2317   169.1 2317.57
   177.5 2316.59184.91872312.752   185.9 2312.32     198 2312.13   211.1 2312.24
213.51162312.734   223.7 2314.01   257.3 2315.21   286.8 2313.49   299.4 2315.91
   303.6  2316.1     322 2315.68     333 2317.19   349.8 2317.22   363.3 2318.11
   379.1 2317.44   395.6 2318.51   457.9 2320.18   615.5 2321.99   714.7 2321.41
#Mann= 3 ,-1,0
       0      .1       0184.9187    .045       0213.5116     .05       0
#XS Ineff= 2 , 0
          150.08 2323.19  364.65         2326.49
Permanent Ineff=
       F       F
Bank Sta=184.9187,213.5116
XS Rating Curve= 0 ,0
Exp/Cntr=0.3,0.1

Type RM Length L Ch R = 1 ,12638   ,308.8,322.4,336.3
XS GIS Cut Line= 3
2258346.95377558485903.9374997172258120.62318352485840.131534936
2257647.49593524485877.452004902
#Sta/Elev= 30
       0 2363.06       7 2361.97    15.4 2359.84      32 2353.71    90.2 2328.08
   115.1 2315.95   144.2 2315.56   177.4 2316.34   198.2 2315.93   231.5 2316.25
   281.2 2315.12   299.8 2315.56   303.8 2315.34   315.9 2313.07   339.9 2313.37
   366.7  2311.7     380 2311.88     389 2310.99   396.1 2310.39   408.7 2310.86
   424.2 2312.54   432.2 2314.42   440.2 2315.37   472.3 2313.74   488.4 2313.85
   492.4 2314.31   508.4 2318.96   516.5 2319.99   544.6 2319.31   709.7 2320.94
#Mann= 4 ,-1,0
       0      .1       0      40     .05       0     389    .045       0
   408.7     .05       0
#XS Ineff= 2 , 0
          177.13 2321.16
Permanent Ineff=
       F       F
Bank Sta=389,408.7
XS Rating Curve= 0 ,0
Exp/Cntr(USF)=0,0
Exp/Cntr=0.3,0.1

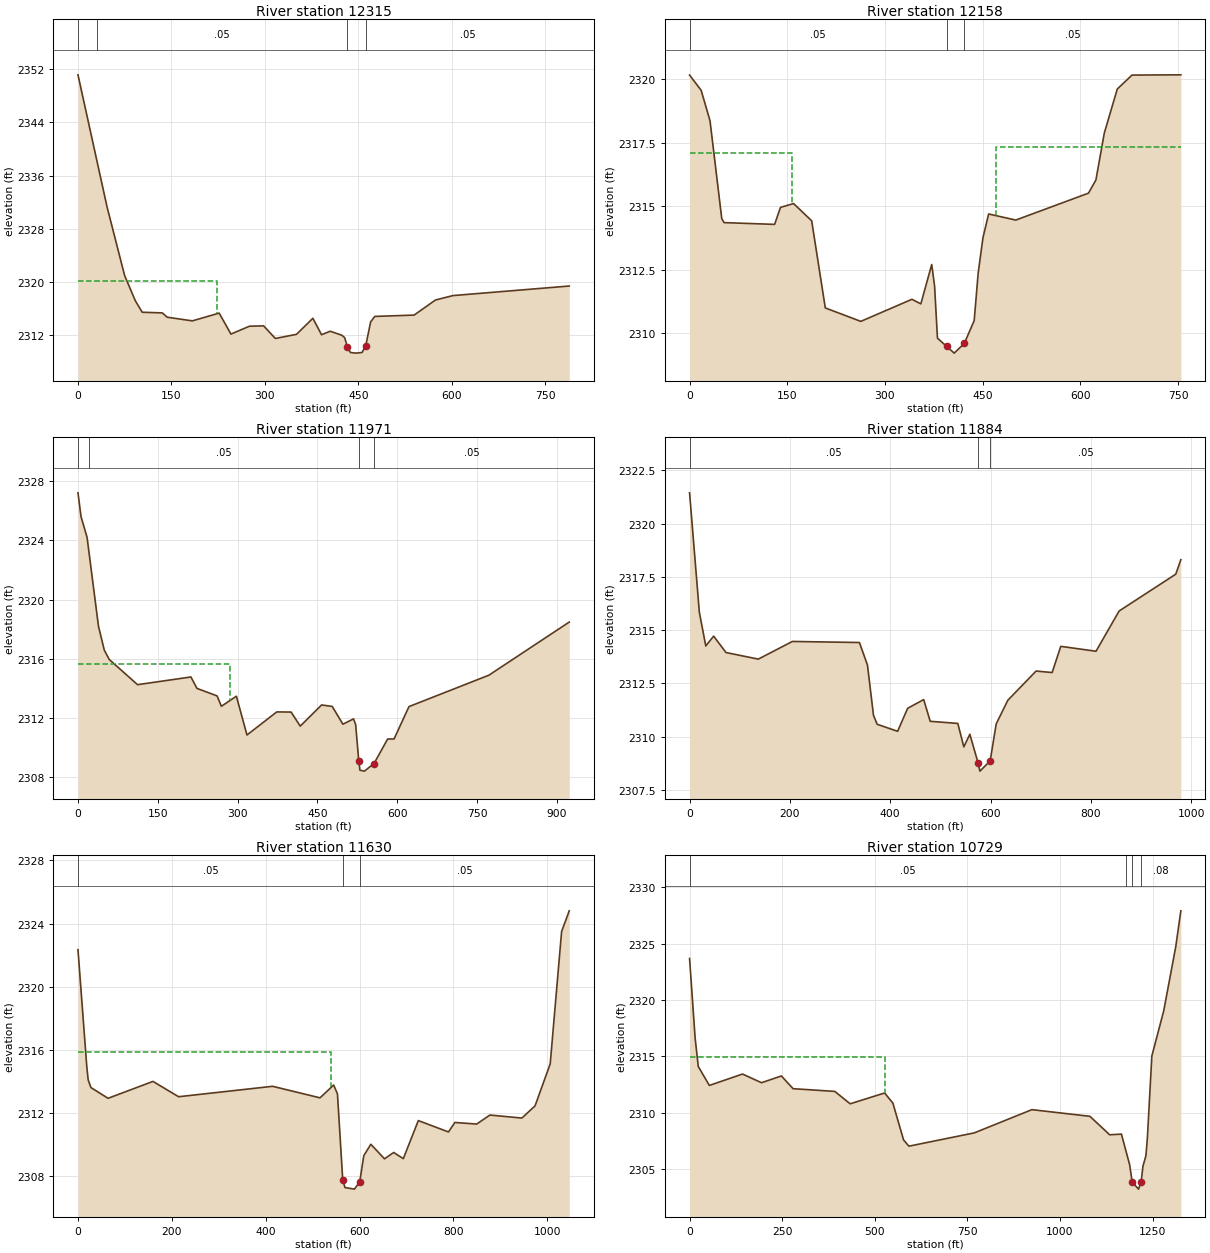
Type RM Length L Ch R = 1 ,12315   ,160.7,157.7,154.8
XS GIS Cut Line= 4
  2258434.540141485681.0448801142258213.41680436485655.188738324
2257976.15684817485516.2861665172257685.95532692485537.244444401
#Sta/Elev= 30
       0 2351.18    46.7 2331.27    74.9 2320.93    92.2 2317.11   103.1 2315.41
   135.3 2315.31   143.3 2314.66   183.6 2314.11   226.6 2315.28   245.5 2312.12
   275.1  2313.3   297.9 2313.36   316.8 2311.46   350.7 2312.08     377  2314.5
   390.9 2312.02   404.8 2312.55   423.4 2311.95     428 2311.59   432.5 2310.18
   437.3 2309.34   446.6 2309.25     456 2309.35   461.8 2310.33   469.7 2313.95
   476.4 2314.78   539.5 2314.98   573.7 2317.25   601.8 2317.92   788.5 2319.36
#Mann= 4 ,-1,0
       0      .1       0      30     .05       0   432.5    .045       0
   461.8     .05       0
#XS Ineff= 2 , 0
          223.55 2320.13
Permanent Ineff=
       F       F
Bank Sta=432.5,461.8
XS Rating Curve= 0 ,0
Exp/Cntr(USF)=0,0
Exp/Cntr=0.3,0.1

Type RM Length L Ch R = 1 ,12158   ,195.5,186.4,179
XS GIS Cut Line= 5
2258471.96912614485556.7925821122258326.07228437485480.640581547
2258128.96258374485419.3892432942258039.96281295485380.247034059
2257761.00801858485443.857654511
#Sta/Elev= 30
       0 2320.17    17.8 2319.57    31.4 2318.37    49.4 2314.52    52.9 2314.36
   130.6 2314.29   139.6 2314.96   159.7 2315.11   187.5 2314.43   208.4    2311
   262.9 2310.47   341.4 2311.34   355.1 2311.16   371.8 2312.71   376.2 2311.86
   380.6 2309.81   394.5 2309.49   406.3 2309.22   421.8  2309.6     437  2310.5
   443.1 2312.37   450.5 2313.77   459.2  2314.7   500.8 2314.46   612.5 2315.52
   623.9 2316.04   636.8 2317.89   656.7 2319.62   679.3 2320.17   754.3 2320.18
#Mann= 3 ,-1,0
       0     .05       0   394.5    .045       0   421.8     .05       0
#XS Ineff= 2 , 0
          156.85 2317.09   471.1         2317.33
Permanent Ineff=
       F       F
Bank Sta=394.5,421.8
XS Rating Curve= 0 ,0
Exp/Cntr(USF)=0,0
Exp/Cntr=0.3,0.1

Type RM Length L Ch R = 1 ,11971   ,88.2,87.1,86.5
XS GIS Cut Line= 4
2258620.47225963485401.0551956092258451.16825377485244.851792868
2257941.34485939485218.321183957 2257765.9014119485169.503278088
#Sta/Elev= 30
       0 2327.21     5.7 2325.61    17.1  2324.2    38.5  2318.2    49.4 2316.59
    58.8 2315.95   111.9 2314.25   212.2 2314.77   223.5    2314   261.4 2313.49
   269.4 2312.79   297.6 2313.47   317.5 2310.85   373.5 2312.41   400.4  2312.4
   417.6 2311.45   457.7 2312.88   477.7 2312.78   497.7 2311.58   517.7 2311.94
   521.7 2311.55  527.552309.101   529.8 2308.47   538.1 2308.41  556.142308.921
   581.8 2310.58   593.8 2310.58   621.9 2312.77     772 2314.89     923 2318.48
#Mann= 4 ,-1,0
       0      .1       0      20     .05       0  527.55    .045       0
  556.14     .05       0
#XS Ineff= 2 , 0
          285.63 2315.65
Permanent Ineff=
       F       F
Bank Sta=527.55,556.14
XS Rating Curve= 0 ,0
Exp/Cntr(USF)=0,0
Exp/Cntr=0.3,0.1

Type RM Length L Ch R = 1 ,11884   ,258,254.3,252
XS GIS Cut Line= 5
 2258652.9009378485343.981937802 2258425.6097409485152.410926646
2257987.18366717485137.4628096932257957.62060183485194.830596268
 2257786.5216343485142.224387229
#Sta/Elev= 30
       0 2321.45    19.5 2315.84    32.3 2314.26      48 2314.72    72.6 2313.95
     137 2313.64     205 2314.47   338.7 2314.42   354.7 2313.36   366.7    2311
   374.1 2310.58   414.8 2310.25   434.8 2311.33   466.8 2311.74   479.8 2310.72
   534.8 2310.62   546.8 2309.52   558.8 2310.11   575.12308.778   578.9 2308.38
   599.32308.862   611.4  2310.6   634.6 2311.71   690.9 2313.08   722.9 2313.01
   740.1 2314.24   810.4 2314.01   856.4  2315.9   969.4 2317.63   979.5 2318.31
#Mann= 3 ,-1,0
       0     .05       0   575.1    .045       0   599.3     .05       0
Bank Sta=575.1,599.3
XS Rating Curve= 0 ,0
Exp/Cntr=0.3,0.1

Type RM Length L Ch R = 1 ,11630   ,857.8,901.1,920.6
XS GIS Cut Line= 4
2258732.47995262485295.3462271672258328.48149101484942.308798442
2257883.46580799484911.0005999762257820.14168462484921.314075888
#Sta/Elev= 30
       0 2322.35    18.8 2314.94    21.7 2314.11    27.6 2313.62    64.1 2312.94
   159.8 2314.01   214.4 2313.04   414.7  2313.7   515.7 2312.97   544.8 2313.78
   552.9 2313.22   564.12307.785   568.9 2307.29     589 2307.19   600.3 2307.65
     609 2309.31     624 2310.03   653.1 2309.11   672.7 2309.51   693.2 2309.12
   725.2 2311.53   789.4 2310.81   803.1 2311.41   849.6 2311.31   877.7 2311.88
   945.8 2311.69   973.9 2312.46  1006.2 2315.12  1030.5  2323.5  1046.8 2324.81
#Mann= 3 ,-1,0
       0     .05       0   564.1    .045       0   600.3     .05       0
#XS Ineff= 2 , 0
          539.49 2315.88
Permanent Ineff=
       F       F
Bank Sta=564.1,600.3
XS Rating Curve= 0 ,0
Exp/Cntr=0.3,0.1

Type RM Length L Ch R = 1 ,10729   ,965.3,957,936.8
XS GIS Cut Line= 5
2258772.76311145485283.2417237852258636.55868716484916.380402411
2258500.11729733484711.3935798522258201.25572458484273.134747385
2258200.58196629484114.883896509
#Sta/Elev= 30
       0 2323.67      15 2316.62    23.5 2314.09    53.4 2312.41     143 2313.42
   194.2 2312.65   247.9 2313.25   279.5 2312.12     392 2311.88   433.6 2310.78
   526.6 2311.74   548.9 2310.84   577.8 2307.57   592.2 2307.02   768.7  2308.2
   924.1 2310.26  1080.8 2309.67  1134.2 2308.03  1165.9 2308.09    1188 2305.38
    1195 2303.83    1212 2303.21  1219.22303.862    1224 2305.25    1232 2306.17
    1236 2307.77    1248 2315.02    1280 2319.02  1312.5 2324.71  1326.3  2327.9
#Mann= 4 ,-1,0
       0     .05       0 1178.03     .08       0    1195    .045       0
  1219.2     .08       0
#XS Ineff= 2 , 0
          527.66 2314.96
Permanent Ineff=
       F       F
Bank Sta=1195,1219.2
XS Rating Curve= 0 ,0
Exp/Cntr(USF)=0,0
Exp/Cntr=0.3,0.1

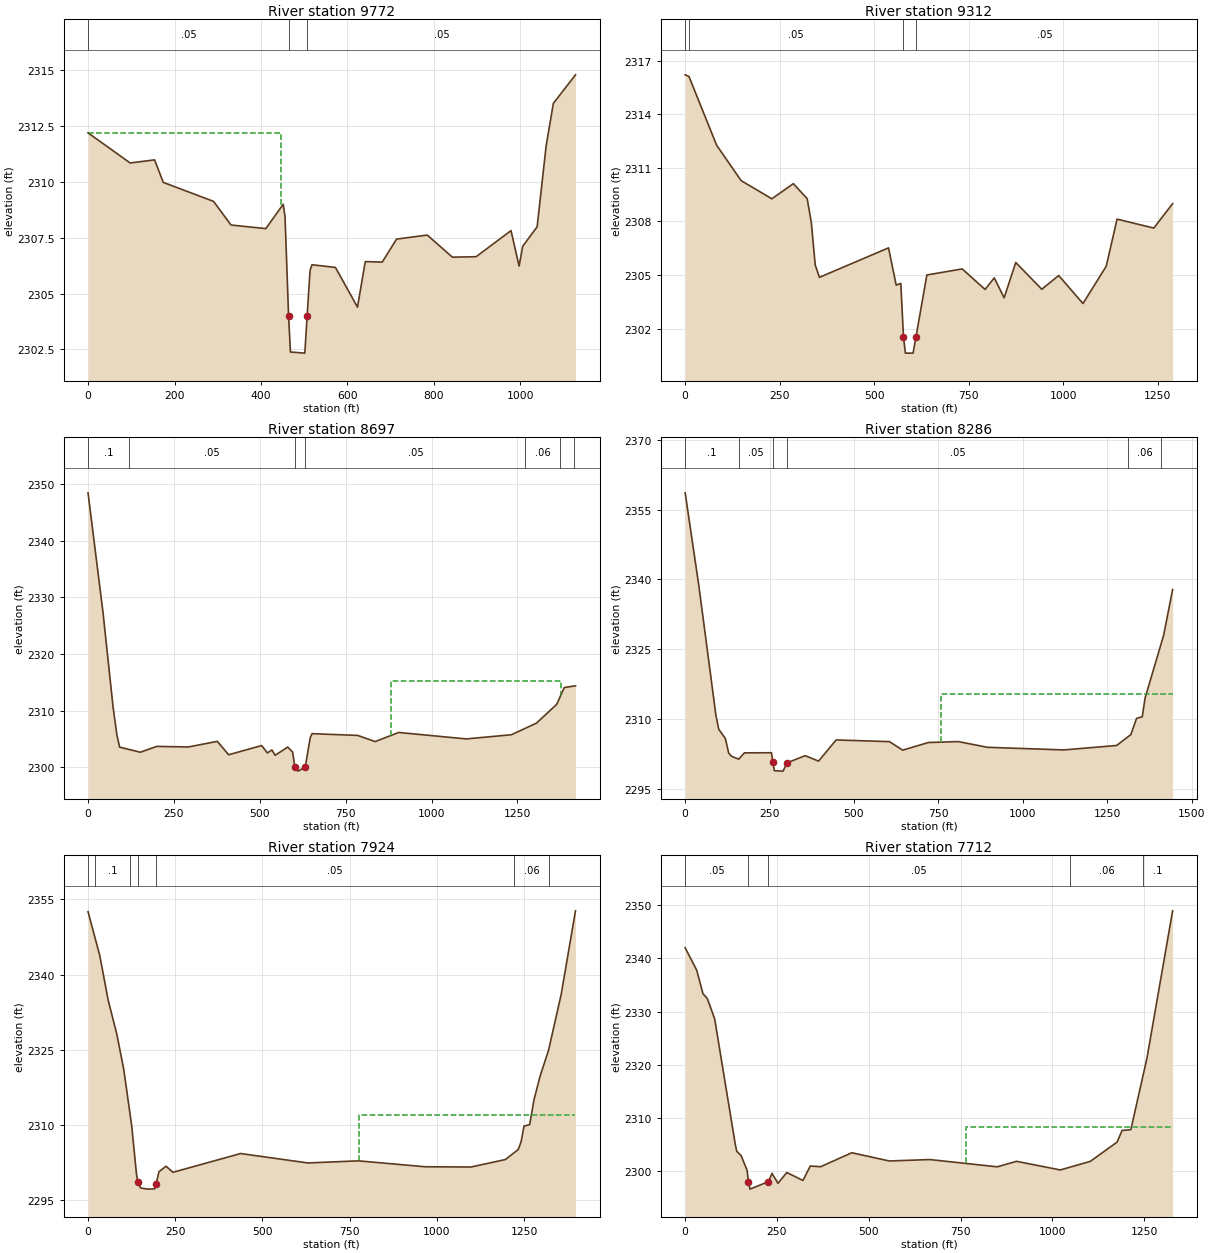
Type RM Length L Ch R = 1 ,9772    ,438.7,459.9,464.5
XS GIS Cut Line= 4
2258916.19955447485106.105585066  2258948.140847484822.335576086
2258932.94081457484656.6116535532258744.54554108484008.004760727
#Sta/Elev= 30
       0  2312.2    97.5 2310.85   153.9 2310.99     174 2309.98   290.3 2309.13
   330.7 2308.07   411.2 2307.91   451.4    2309   455.6 2308.45   463.9 2303.98
   468.1 2302.38   501.4 2302.33  506.782304.008   513.5 2306.03     518 2306.29
   572.2 2306.17   623.2 2304.39   641.2 2306.43   680.5 2306.41   713.6 2307.44
   784.6 2307.62   842.7 2306.63   897.6 2306.65   978.3 2307.82     997 2306.23
  1005.4 2307.12  1038.7 2307.99  1059.5 2311.61  1076.2 2313.52  1127.4  2314.8
#Mann= 3 ,-1,0
       0     .05       0   463.9    .045       0  506.78     .05       0
#XS Ineff= 2 , 0
          446.99  2312.2
Permanent Ineff=
       F       F
Bank Sta=463.9,506.78
XS Rating Curve= 0 ,0
Exp/Cntr=0.3,0.1

Type RM Length L Ch R = 1 ,9312    ,595.1,614.7,625.8
XS GIS Cut Line= 4
2259091.65027824 485158.99019501 2259183.3968222484637.048874456
2259249.62589114484235.4125066912259308.48388916483888.019165508
#Sta/Elev= 30
       0 2316.22      10 2316.13    83.1 2312.28     148 2310.29   229.3 2309.27
   286.1 2310.12   322.7 2309.28   333.6 2307.96     344 2305.56   355.2 2304.87
   537.9 2306.52   558.2 2304.43   570.4 2304.53   577.4 2301.54   582.5 2300.62
   602.8 2300.62   610.6 2301.54   639.3    2305   732.7 2305.34   793.3 2304.19
   817.6 2304.84   843.7 2303.72   874.4  2305.7   943.3  2304.2     988 2304.97
  1052.2  2303.4  1113.7 2305.49  1142.4 2308.13  1239.6 2307.63  1289.3    2309
#Mann= 4 ,-1,0
       0      .1       0      10     .05       0   577.4    .045       0
   610.6     .05       0
Bank Sta=577.4,610.6
XS Rating Curve= 0 ,0
Exp/Cntr=0.3,0.1

Type RM Length L Ch R = 1 ,8697    ,426.7,411.2,391.5
XS GIS Cut Line= 4
 2259510.7117432485072.8025861972259541.24026772484564.913328946
2259687.89756504 484422.44493466 2259793.9722679 483724.84116169
#Sta/Elev= 30
       0 2348.46    43.7 2327.26    72.8 2310.66    83.8 2305.77    91.8 2303.53
   152.2 2302.63     200 2303.66   292.1 2303.56   376.3 2304.55   409.3 2302.18
   505.4 2303.81     522 2302.51   535.2 2303.03   544.6 2302.09   581.4 2303.54
   595.6 2302.64   602.1 2299.97   611.8 2299.29   632.3 2300.03   646.7 2305.16
   652.1 2305.91   784.9  2305.6   835.9 2304.51   904.3 2306.12  1100.9 2304.98
  1232.4 2305.72  1305.3 2307.77  1364.3 2311.09  1386.2 2314.06  1418.9 2314.36
#Mann= 7 ,-1,0
       0      .1       0     120     .05       0   602.1    .045       0
   632.3     .05       0 1273.27     .06       0 1373.27      .1       0
 1413.27     .06       0
#XS Ineff= 1 ,-1
   881.4  1375.7 2315.17
Permanent Ineff=
       F
Bank Sta=602.1,632.3
XS Rating Curve= 0 ,0
Exp/Cntr(USF)=0,0
Exp/Cntr=0.3,0.1

Type RM Length L Ch R = 1 ,8286    ,368.4,362.3,351.1
XS GIS Cut Line= 2
2259683.47223485485103.3708251442260146.36779448 483736.04855672
#Sta/Elev= 30
       0 2358.61    40.3 2338.76      91 2310.83    99.4  2307.8     119  2305.8
     129 2302.64   137.5 2301.97   158.6 2301.37   175.5 2302.72   255.7 2302.74
   259.9 2300.65   264.1 2298.88   289.7 2298.79     302 2300.58   355.6 2302.11
   395.1 2300.94   447.1 2305.49   604.9 2305.13   644.2  2303.3   720.2 2304.94
   808.9 2305.14   895.1 2303.91  1121.4 2303.35  1277.7  2304.3  1319.9 2306.64
  1336.8 2310.13  1353.7 2310.47  1362.1 2314.51    1417 2327.98  1443.6 2337.82
#Mann= 6 ,-1,0
       0      .1       0     160     .05       0   259.9    .045       0
     302     .05       0    1310     .06       0    1410      .1       0
#XS Ineff= 2 , 0
                          757.48          2315.4
Permanent Ineff=
       F       F
Bank Sta=259.9,302
XS Rating Curve= 0 ,0
Exp/Cntr(USF)=0,0
Exp/Cntr=0.3,0.1

Type RM Length L Ch R = 1 ,7924    ,218.5,211.4,207
XS GIS Cut Line= 3
2260040.87964509485162.6701368112260100.49841817484724.218200469
2260314.07639366483793.163670252
#Sta/Elev= 30
       0 2352.56    33.8 2343.76      58 2334.82    82.2 2328.24   102.4 2321.12
   125.1 2309.91   138.8  2300.3   142.8 2298.55   150.9 2297.45   171.3 2297.22
   191.2 2297.29   195.3  2298.3   203.3 2300.68   223.5 2301.79   243.7 2300.58
   437.5 2304.32   630.3 2302.44   775.2 2302.86   966.8 2301.68  1098.1 2301.63
  1196.6 2303.12  1233.6 2305.12  1241.8 2306.67    1250 2309.78  1266.4  2310.1
  1278.7 2315.04    1296  2319.7  1320.4  2324.9  1356.7 2336.06  1397.7 2352.73
#Mann= 7 ,-1,0
       0     .05       0      20      .1       0     120     .05       0
   142.8    .045       0   195.3     .05       0 1222.49     .06       0
 1322.49      .1       0
#XS Ineff= 2 , 0
                          776.74         2312.08
Permanent Ineff=
       F       F
Bank Sta=142.8,195.3
XS Rating Curve= 0 ,0
Exp/Cntr(USF)=0,0
Exp/Cntr=0.3,0.1

Type RM Length L Ch R = 1 ,7712    ,459.1,454,449.1
XS GIS Cut Line= 3
2260284.78114166485193.5313510822260264.83136541484786.236904313
2260451.34499698483885.781250607
#Sta/Elev= 30
       0 2342.02    31.5 2337.78    48.4 2333.38    60.4 2332.43    80.4 2328.62
   136.5 2304.98   140.5 2303.69   152.5 2302.85   168.6 2300.12   172.4 2297.91
   176.6 2296.56   226.92297.972   236.6 2299.53   252.7 2297.65   276.7 2299.69
   320.7 2298.19   340.7 2300.91   368.8 2300.78   453.8 2303.41   555.9 2301.86
   666.2 2302.13     850 2300.76   902.2  2301.8  1021.6 2300.17  1103.3 2301.79
  1176.3 2305.42  1189.8 2307.61  1213.6 2307.75  1257.5 2321.21  1327.4 2348.97
#Mann= 5 ,-1,0
       0     .05       0   172.4    .045       0   226.9     .05       0
 1047.78     .06       0 1247.78      .1       0
#XS Ineff= 2 , 0
                          765.12         2308.31
Permanent Ineff=
       F       F
Bank Sta=172.4,226.9
XS Rating Curve= 0 ,0
Exp/Cntr(USF)=0,0
Exp/Cntr=0.3,0.1

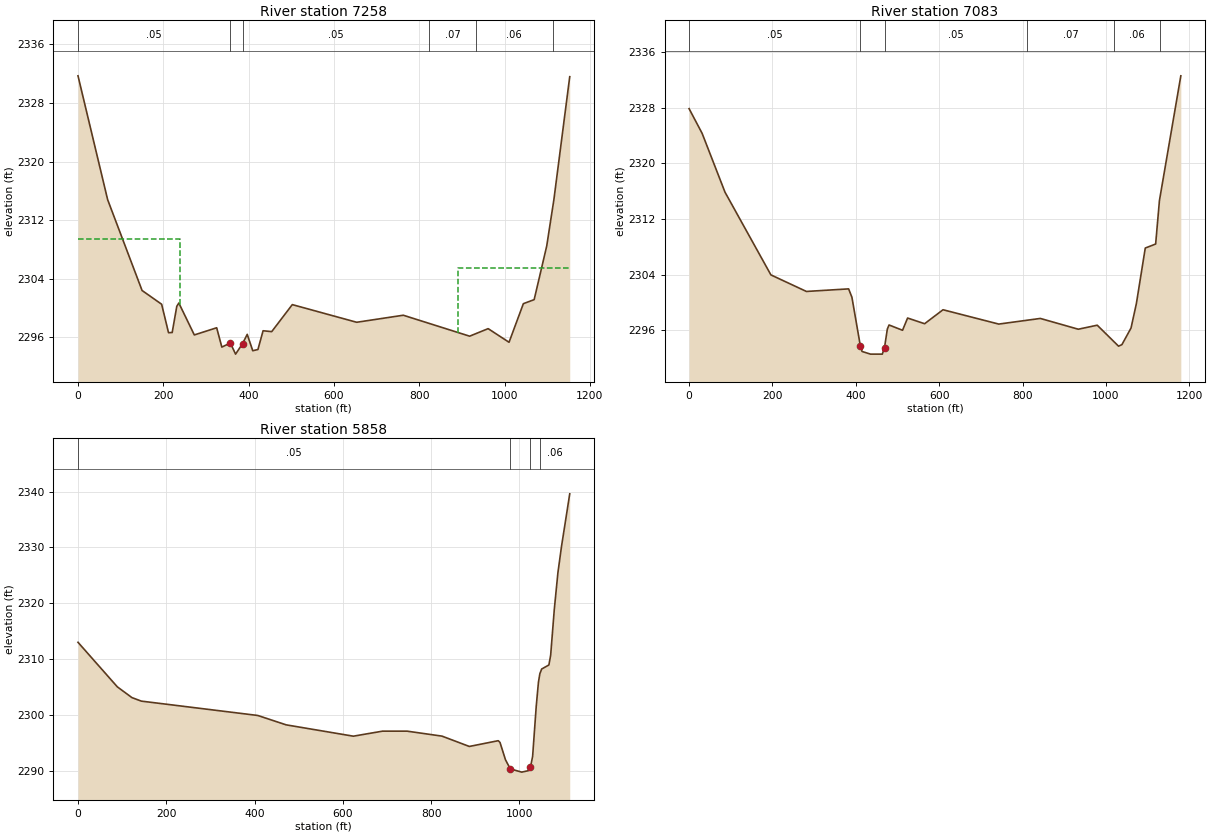
Type RM Length L Ch R = 1 ,7258    ,184,175.3,173.7
XS GIS Cut Line= 4
2260662.18134589485248.1901048922260735.30582331485098.333802227
 2260693.0482074484755.0684390182260889.54562617 484145.78230373
#Sta/Elev= 30
       0 2331.71    69.5  2314.8   150.2  2302.4   196.1 2300.52   212.2 2296.64
   220.8 2296.66   231.6 2300.24   236.4 2300.69   272.7 2296.33   325.1 2297.31
   337.2 2294.67   357.2 2295.23   369.4 2293.71   385.9 2295.15   396.7 2296.41
   409.7 2294.17   421.8 2294.34   433.9  2296.9   454.1 2296.78   502.4 2300.47
   653.3 2298.06   762.6 2299.02   918.1 2296.16   961.5 2297.19  1010.5 2295.33
  1044.1  2300.6  1069.4 2301.15  1098.8 2308.46  1115.6 2314.79  1152.8 2331.59
#Mann= 6 ,-1,0
       0     .05       0   357.2    .045       0   385.9     .05       0
   822.6     .07       0   932.6     .06       0  1112.6      .1       0
#XS Ineff= 2 , 0
          238.33 2309.41  891.03         2305.46
Permanent Ineff=
       F       F
Bank Sta=357.2,385.9
XS Rating Curve= 0 ,0
Exp/Cntr(USF)=0,0
Exp/Cntr=0.3,0.1

Type RM Length L Ch R = 1 ,7083    ,1209.5,1225.3,1235.7
XS GIS Cut Line= 4
2260801.94953217485328.3549205432260915.39455163485126.461241846
2260842.32826791484653.4531946132261005.76600781 484213.13269536
#Sta/Elev= 30
       0 2327.85    31.2 2324.31    86.2 2315.84   196.3 2303.95   281.5 2301.57
   382.8 2301.94   390.7 2300.74   410.8 2293.79     415 2292.94   435.3 2292.56
   463.6 2292.56   468.92293.505   475.7 2296.16   479.8 2296.75   512.2 2295.99
   524.3 2297.75   565.1 2296.93   609.3 2298.94     743 2296.88   842.8 2297.69
   933.9 2296.14   979.3 2296.72  1030.5  2293.7  1038.6 2293.93  1060.4 2296.31
  1073.2 2299.81  1094.6 2307.81  1119.5 2308.39  1128.6 2314.65  1179.9 2332.57
#Mann= 6 ,-1,0
       0     .05       0   410.8    .045       0   468.9     .05       0
   810.2     .07       0  1020.2     .06       0  1130.2      .1       0
Bank Sta=410.8,468.9
XS Rating Curve= 0 ,0
Exp/Cntr(USF)=0,0
Exp/Cntr=0.3,0.1

Type RM Length L Ch R = 1 ,5858    ,477.3,493.7,505.7
XS GIS Cut Line= 3
2260905.79650855485260.5692449432261248.95668561484874.020999519
2261378.63021109484291.048065965
#Sta/Elev= 30
       0 2313.01    89.1 2305.03   122.2  2303.1   143.6 2302.47   407.3  2299.9
   471.6 2298.22   623.8 2296.19   689.9 2297.09   745.6 2297.09   824.7  2296.2
   886.6 2294.35   952.1 2295.38   956.1 2295.07   968.5 2291.96   979.5 2290.32
  1005.4 2289.75  1021.8 2290.04    1025  2290.6    1030 2292.56  1038.2 2301.55
  1043.2 2305.86  1046.4 2307.38  1050.5 2308.22  1066.9 2308.95    1070 2310.31
    1071 2310.81  1079.1  2318.9  1087.3 2325.47  1095.5 2330.21  1114.1 2339.61
#Mann= 4 ,-1,0
       0     .05       0   979.5    .045       0    1025     .05       0
 1046.89     .06       0
Bank Sta=979.5,1025
XS Rating Curve= 0 ,0
Exp/Cntr(USF)=0,0
Exp/Cntr=0.3,0.1