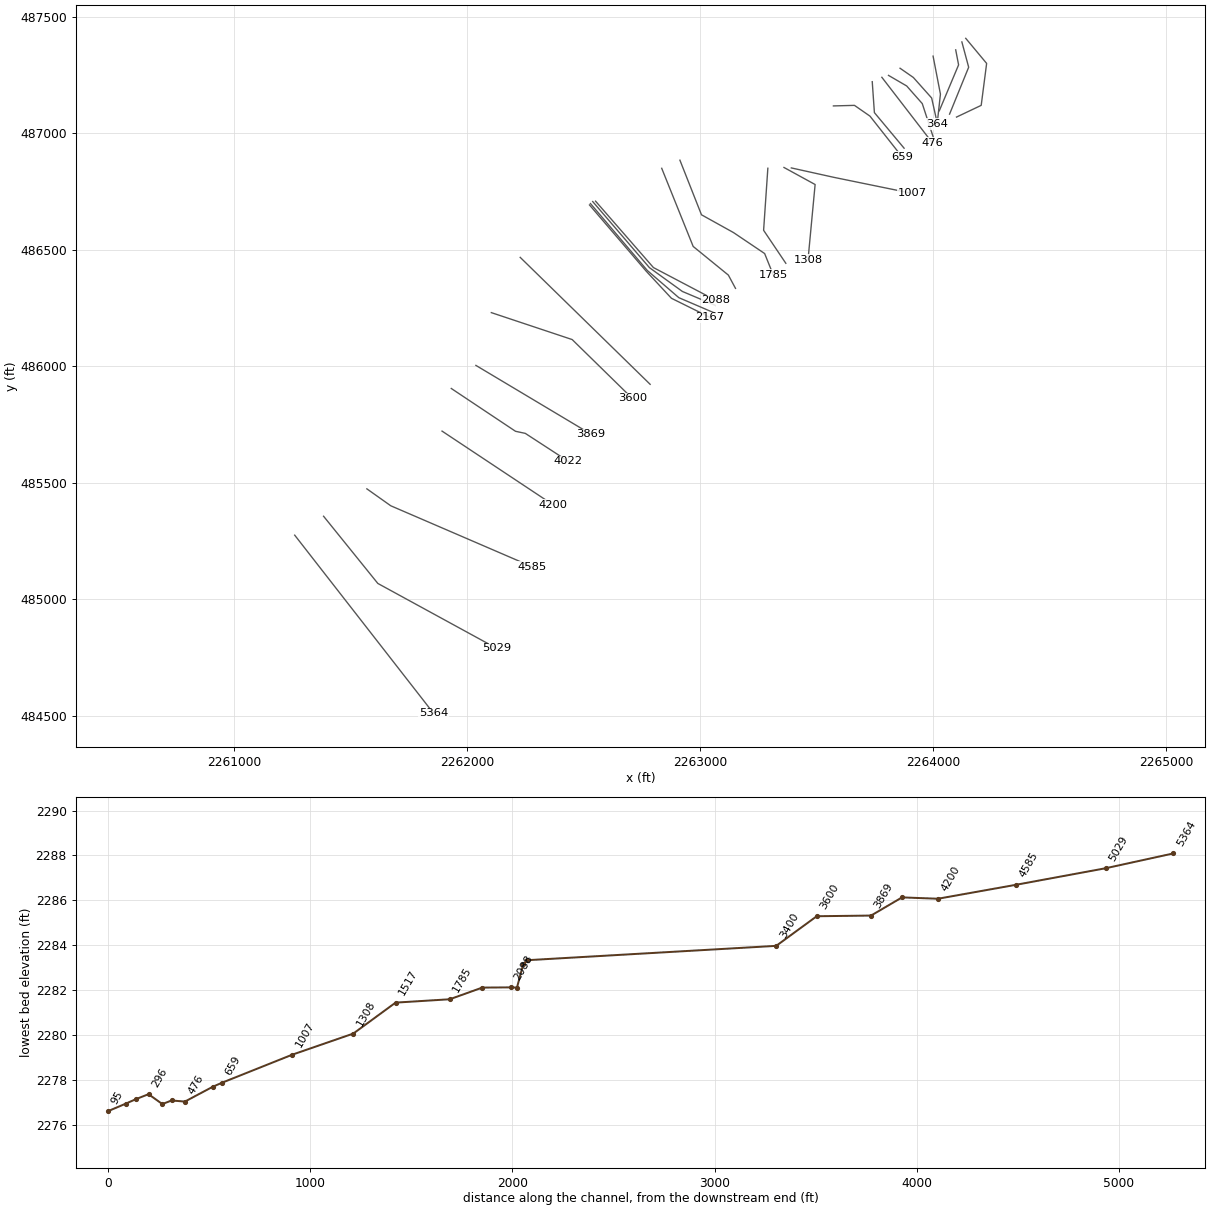
HEC-RAS study CLOVERCK.prj: CLOVERCK

--- CLOVERCK.g01 (geometry) --- (continued)

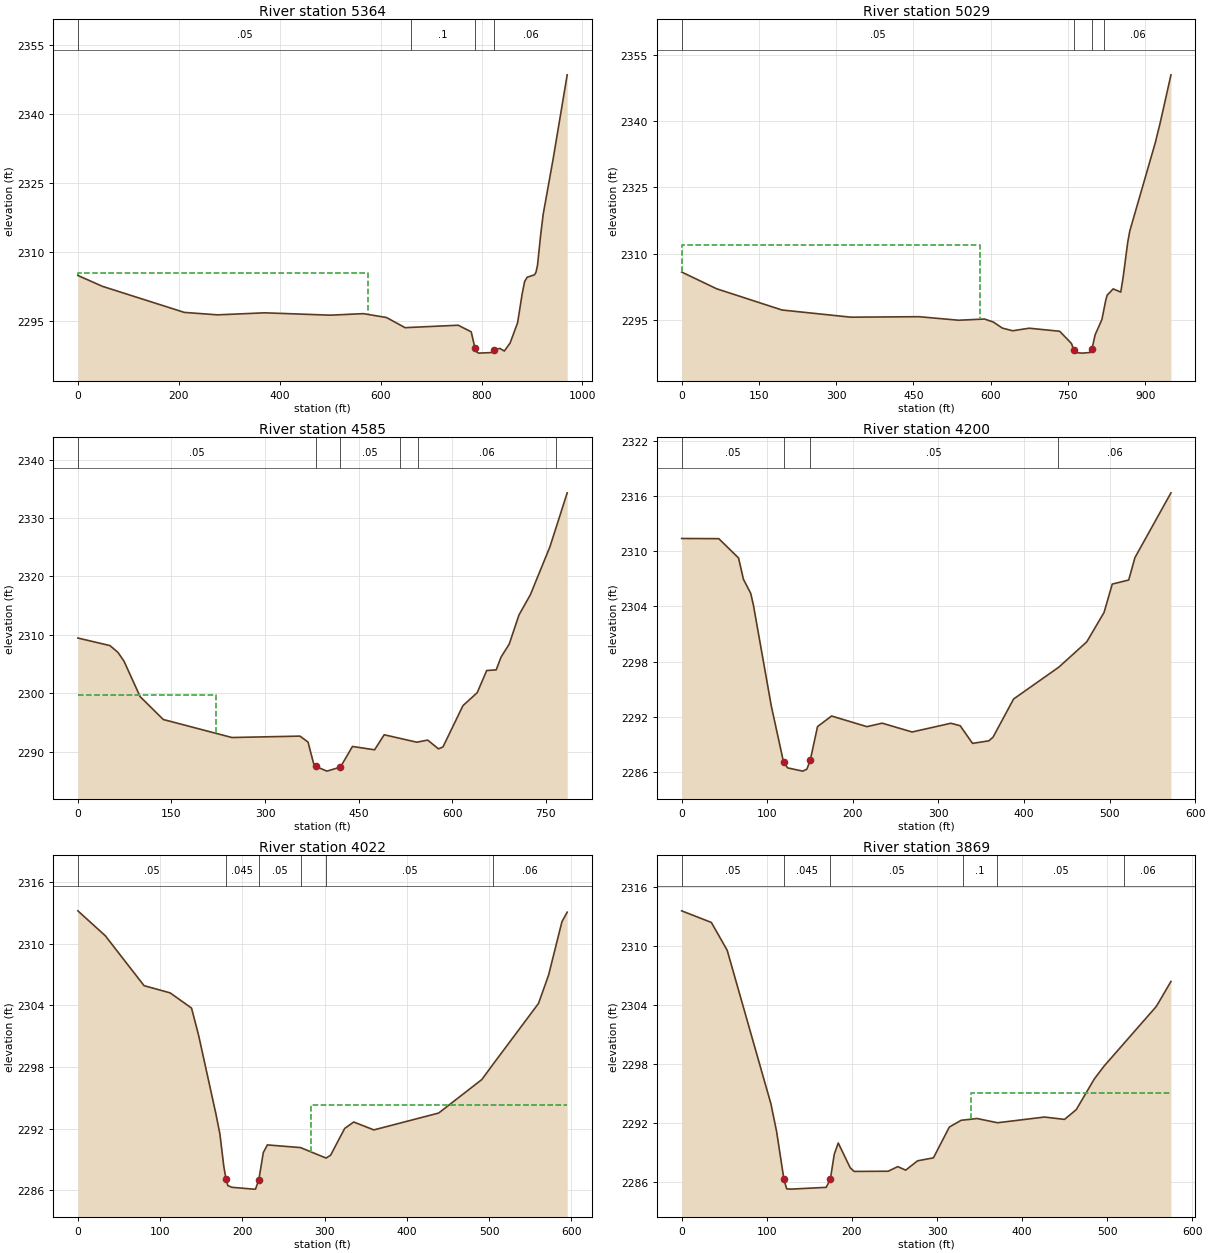
Type RM Length L Ch R = 1 ,5364    ,323.6,334.7,346
XS GIS Cut Line= 2
2261260.54922042 485275.569522262261856.61627181484510.723628361
#Sta/Elev= 30
       0 2304.93    48.7 2302.57     211 2296.92   276.9 2296.39   370.3 2296.83
   500.2 2296.32   565.9 2296.65   611.6 2295.81   648.4 2293.61   753.6 2294.14
   779.5 2292.71   786.8 2289.24   789.1 2288.47   793.8 2288.09   819.3 2288.21
   825.1 2288.85   836.5 2289.11   845.1 2288.54   856.5 2290.27   871.4 2294.67
   880.4  2300.9   885.4 2303.64   890.5 2304.55   904.9 2305.07   907.8 2305.62
   910.8 2307.09   916.9  2313.5     922 2318.12     942  2330.3   969.7 2348.43
#Mann= 4 ,-1,0
       0     .05       0     660      .1       0   786.8    .045       0
   825.1     .06       0
#XS Ineff= 2 , 0
          574.98 2305.44
Permanent Ineff=
       F       F
Bank Sta=786.8,825.1
XS Rating Curve= 0 ,0
Exp/Cntr(USF)=0,0
Exp/Cntr=0.3,0.1

Type RM Length L Ch R = 1 ,5029    ,446.5,444.7,448.6
XS GIS Cut Line= 3
2261384.46280099485356.7542819482261617.33487483485068.334740952
 2262125.8078434484790.597405179
#Sta/Elev= 30
       0 2305.82    67.8 2302.03   194.8 2297.21   328.5 2295.58   460.7 2295.69
     538 2294.89   588.1 2295.16     605 2294.49   622.7 2293.11   642.8  2292.5
   674.7 2293.08     734 2292.39   756.8 2289.63   761.6 2288.15   765.9 2287.54
   777.8 2287.43   793.3 2287.57   796.6 2288.32   802.8 2291.57     816 2295.05
   823.2 2299.28   826.1 2300.55   837.9    2302   852.6 2301.27   857.1 2304.54
   866.2 2312.61   870.3  2315.2   919.7 2335.16   929.3 2339.72   950.1 2350.54
#Mann= 4 ,-1,0
       0     .05       0   761.6    .045       0   796.6     .05       0
   820.7     .06       0
#XS Ineff= 2 , 0
          579.94 2312.06
Permanent Ineff=
       F       F
Bank Sta=761.6,796.6
XS Rating Curve= 0 ,0
Exp/Cntr(USF)=0,0
Exp/Cntr=0.3,0.1

Type RM Length L Ch R = 1 ,4585    ,385.1,385,379
XS GIS Cut Line= 3
2261570.33317185485474.2585393912261672.88234199485401.619543881
2262277.49515756485140.973736462
#Sta/Elev= 30
       0 2309.46    51.3 2308.17    64.1 2307.02    73.8 2305.53    99.7 2299.44
   136.9 2295.52   246.9 2292.44   355.8 2292.68   368.8 2291.67   377.5 2288.08
   381.1  2287.5   399.1 2286.69   420.7 2287.38     440 2290.91   475.5 2290.34
   490.8 2292.91   543.1 2291.64   560.5    2292   577.9  2290.5   585.1 2290.84
   617.1  2297.9   639.9 2300.11   655.1  2303.9   670.3 2304.01   678.1  2306.2
   691.2 2308.42   706.8  2313.4   725.1 2316.87   756.5 2325.09   784.1  2334.3
#Mann= 6 ,-1,0
       0     .05       0   381.1    .045       0   420.7     .05       0
  515.67      .1       0  545.67     .06       0  765.67      .1       0
#XS Ineff= 2 , 0
          220.85 2299.75
Permanent Ineff=
       F       F
Bank Sta=381.1,420.7
XS Rating Curve= 0 ,0
Exp/Cntr(USF)=0,0
Exp/Cntr=0.3,0.1

Type RM Length L Ch R = 1 ,4200    ,177.2,177.8,176.4
XS GIS Cut Line= 2
2261892.93576956485722.0857005422262369.36212246485405.892425969
#Sta/Elev= 30
       0 2311.39    43.4 2311.37    66.5 2309.27    72.2 2306.95    80.7 2305.42
    83.8 2304.17   104.7 2293.19   119.1 2287.04   123.9 2286.42   141.5 2286.07
   146.3 2286.28   150.2 2287.23   158.8 2290.92   175.2 2292.07   216.5 2290.91
   234.3 2291.29   269.3 2290.33   314.6 2291.28   325.5 2291.01   339.9 2289.09
   359.1 2289.37   363.9 2289.77   387.9 2293.92   440.8 2297.39   473.4 2300.14
   493.6 2303.34   503.2 2306.43   522.4 2306.87   529.7 2309.31   571.8 2316.36
#Mann= 4 ,-1,0
       0     .05       0   119.1    .045       0   150.2     .05       0
     440     .06       0
Bank Sta=119.1,150.2
XS Rating Curve= 0 ,0
Exp/Cntr(USF)=0,0
Exp/Cntr=0.3,0.1

Type RM Length L Ch R = 1 ,4022    ,151.7,153.1,151.9
BEGIN DESCRIPTION:
Conservative IFA added to fix the draw down
END DESCRIPTION:
XS GIS Cut Line= 4
2261932.48220764485905.0643334372262208.25773692485721.299191104
 2262250.2048971485712.3596323792262435.18499687485592.019418774
#Sta/Elev= 30
       0  2313.2    33.3 2310.78    80.5 2305.92   112.2 2305.22   138.2 2303.74
   146.8  2301.1   167.9 2293.43   172.7 2291.49   177.5 2288.31   180.1 2287.13
   182.3 2286.48   187.1 2286.31   213.2 2286.13     216 2286.13  220.04 2287.05
   225.5 2289.69   230.4 2290.43   270.8 2290.17   301.8 2289.15   307.3 2289.43
   324.4 2292.03   335.4 2292.66   359.9 2291.89   438.7 2293.53   491.2 2296.79
   504.8 2298.27   560.1 2304.19   572.3 2306.93   588.6 2312.14     595 2313.07
#Mann= 6 ,-1,0
       0     .05       0   180.1    .045       0  220.04     .05       0
   270.8      .1       0   301.8     .05       0   504.8     .06       0
#XS Ineff= 2 , 0
                          283.06         2294.34
Permanent Ineff=
       F       F
Bank Sta=180.1,220.04
XS Rating Curve= 0 ,0
Exp/Cntr(USF)=0,0
Exp/Cntr=0.5,0.3

Type RM Length L Ch R = 1 ,3869    ,261.1,268.8,277
XS GIS Cut Line= 2
2262038.21376058486004.0959184052262531.73164184485709.267054276
#Sta/Elev= 30
       0 2313.62    34.9 2312.44    53.5 2309.61   104.8 2294.02   111.5 2291.21
   120.2  2286.3   123.4 2285.35   128.1 2285.32   169.8  2285.5   174.7 2286.32
   179.3 2288.87     184 2290.01     198  2287.5   202.6 2287.12   242.7 2287.14
   253.9 2287.61   263.2 2287.25   277.2  2288.2   295.8  2288.5   314.5 2291.63
   328.4 2292.32   347.1  2292.5   371.1 2292.07   426.3 2292.65   449.8 2292.41
   463.6  2293.4   484.8 2296.52   496.5 2297.85   557.8 2303.91   574.9 2306.44
#Mann= 6 ,-1,0
       0     .05       0   120.2    .045       0   174.7     .05       0
     330      .1       0     370     .05       0     520     .06       0
#XS Ineff= 2 , 0
                          339.72         2295.06
Permanent Ineff=
       F       F
Bank Sta=120.2,174.7
XS Rating Curve= 0 ,0
Exp/Cntr(USF)=0,0
Exp/Cntr=0.3,0.1

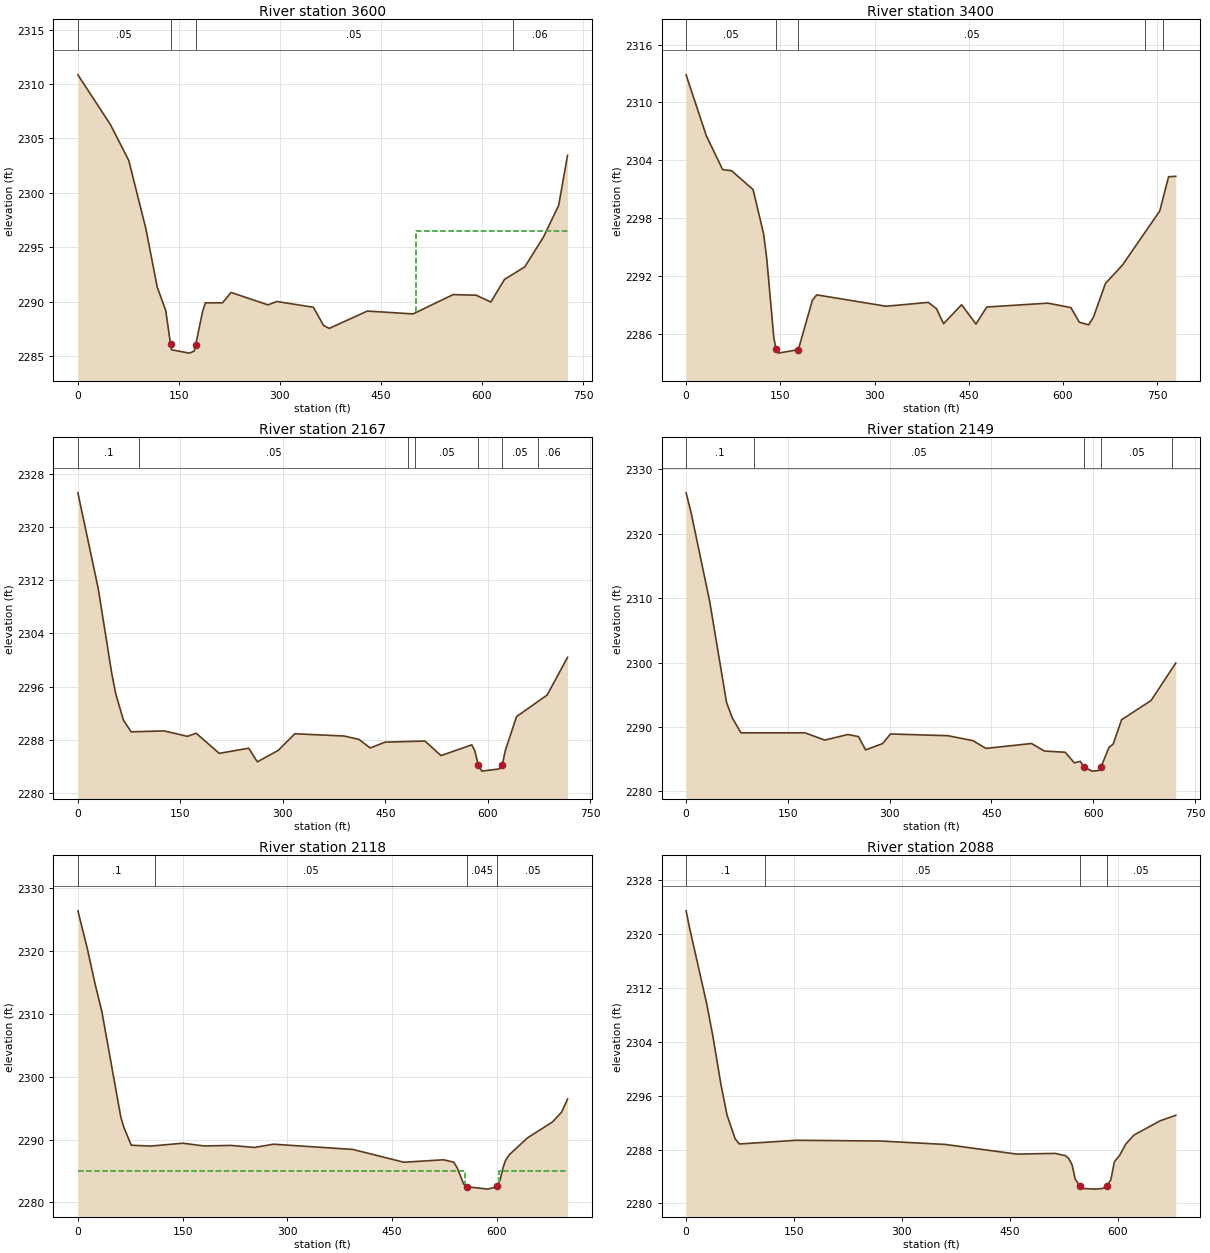
Type RM Length L Ch R = 1 ,3600    ,212.3,200.2,186.9
XS GIS Cut Line= 3
2262104.44343296486230.5586691132262451.39878834486114.965943701
2262709.59568164485862.229684721
#Sta/Elev= 30
       0 2310.84    48.3 2306.27    75.6 2302.97   100.9 2296.72   117.8 2291.35
   130.4 2289.21  137.622286.086   138.9  2285.6   165.3 2285.29   172.6 2285.47
   174.8 2286.04   185.2 2289.13   189.4 2289.91   214.7 2289.91   227.4 2290.86
   282.2 2289.72   295.4 2290.03   349.7  2289.5   364.6 2287.84   373.2 2287.56
   429.7 2289.15   497.6 2288.89     557 2290.66   591.3 2290.61   613.1 2289.98
   633.4 2292.06   663.5 2293.21   691.4 2295.96   713.8 2298.85     727 2303.45
#Mann= 4 ,-1,0
       0     .05       0  137.62    .045       0   174.8     .05       0
   645.7     .06       0
#XS Ineff= 2 , 0
                          502.33         2296.51
Permanent Ineff=
       F       F
Bank Sta=137.62,174.8
XS Rating Curve= 0 ,0
Exp/Cntr(USF)=0,0
Exp/Cntr=0.3,0.1

Type RM Length L Ch R = 1 ,3400    ,1224.4,1232.7,1237.4
XS GIS Cut Line= 2
2262228.35701353486467.7036250432262785.96812613485922.911158717
#Sta/Elev= 30
       0 2312.87    32.2 2306.54    58.2 2303.03    72.4 2302.91   106.6 2300.96
   123.3  2296.4   128.4 2293.79   139.6 2285.62   143.1 2284.39   146.7 2283.97
   178.7 2284.33   201.1 2289.47   208.1 2290.02   318.4 2288.84   385.6 2289.24
   398.6 2288.59     410 2287.03   438.6    2289   461.5 2286.99   478.7 2288.76
     576 2289.16   612.6  2288.7   626.1 2287.18   640.9 2286.91   648.4 2287.68
   667.6  2291.2   694.7 2293.11   754.1 2298.73   768.2 2302.29   779.6 2302.33
#Mann= 5 ,-1,0
       0     .05       0   143.1    .045       0   178.7     .05       0
     730     .06       0     760      .1       0
Bank Sta=143.1,178.7
XS Rating Curve= 0 ,0
Exp/Cntr(USF)=0,0
Exp/Cntr=0.3,0.1

Type RM Length L Ch R = 1 ,2167    ,18.2,18.5,20.7
BEGIN DESCRIPTION:
xs 4
END DESCRIPTION:
XS GIS Cut Line= 4
2262525.66150944486692.6430664692262768.25388531486409.347271826
2262877.33904762486292.1214257672263041.78085945486210.714588226
#Sta/Elev= 30
       0 2325.11    29.8 2310.72    49.6 2297.96    55.3 2294.97    66.7 2290.96
      78 2289.23   126.2 2289.37   160.3 2288.55   173.1 2289.02   206.8    2286
   249.9 2286.77   262.6 2284.73   292.9 2286.42   317.5 2288.94   389.6  2288.6
   411.4 2288.09   427.8 2286.81   449.7 2287.68   507.9 2287.85   531.4 2285.66
   576.4 2287.28   580.9 2286.39   585.9 2284.26   591.2 2283.33   616.6 2283.66
   621.1 2284.26   625.5 2286.41   641.9 2291.51   686.7 2294.75   716.6 2300.41
#Mann= 7 ,-1,0
       0      .1       0      90     .05       0  482.97     .06       0
  492.97     .05       0   585.9    .045       0   621.1     .05       0
   673.1     .06       0
Bank Sta=585.9,621.1
XS Rating Curve= 0 ,0
Exp/Cntr(USF)=0,0
Exp/Cntr=0.5,0.3

Type RM Length L Ch R = 1 ,2149    ,35.7,30.8,30.9
BEGIN DESCRIPTION:
xs 3
END DESCRIPTION:
XS GIS Cut Line= 4
2262529.74475167486698.7383595852262773.74768335486411.472496754
 2262909.0515039486294.7502471242263061.46548764486229.333701353
#Sta/Elev= 30
       0 2326.37     7.3 2323.32    34.6  2309.6    59.6 2293.81    68.1 2291.41
    80.8  2289.1   175.2  2289.1   204.3 2287.97   238.5 2288.84     254 2288.51
   264.5 2286.45   289.4 2287.42   301.2 2288.92   385.9 2288.65   422.8 2287.88
   441.7 2286.68     509 2287.44     528 2286.27   558.6 2286.08   572.1 2284.43
   580.8 2284.67   586.6 2283.76   598.2 2283.15   606.9 2283.22   611.2 2283.74
   623.1 2286.84   629.2 2287.34   641.7 2291.13   685.2 2294.12   721.5 2299.94
#Mann= 5 ,-1,0
       0      .1       0     100     .05       0   586.6    .045       0
   611.2     .05       0   715.6     .06       0
#XS Ineff= 2 , 0
             567    2285     623          2284.7
Permanent Ineff=
       F       F
Bank Sta=586.6,611.2
XS Rating Curve= 0 ,0
Exp/Cntr(USF)=0,0
Exp/Cntr=0.5,0.3

Type RM Length L Ch R = 1 ,2118    ,32.9,30.2,27.9
BEGIN DESCRIPTION:
xs 2
END DESCRIPTION:
XS GIS Cut Line= 4
2262539.48057137486707.2359958652262782.69606131  486423.8195985
2262924.45451113486321.357535694 2263065.1476369486261.870242928
#Sta/Elev= 30
       0 2326.41    13.3 2320.49    24.6 2314.77    34.3 2310.38    61.5 2293.55
      66 2291.88    76.5  2289.1   104.1 2288.96   150.3 2289.42   180.7 2288.98
   218.8 2289.07   252.9 2288.74   279.9 2289.26   393.6 2288.43   466.7 2286.39
   523.4 2286.78   538.2  2286.4   543.1 2285.51   552.4 2282.91   557.5 2282.48
   587.2 2282.11   600.2 2282.53   604.5 2283.57   608.9 2285.56   612.4  2286.7
   617.6 2287.57   643.6 2290.26   679.6 2292.81   692.6 2294.37   701.1 2296.44
#Mann= 4 ,-1,0
       0      .1       0     110     .05       0   557.5    .045       0
   600.2     .05       0
#XS Ineff= 2 , 0
          554.91 2285.02  602.31         2284.96
Permanent Ineff=
       F       F
Bank Sta=557.5,600.2
XS Rating Curve= 0 ,0
Exp/Cntr(USF)=0,0
Exp/Cntr=0.5,0.3

Type RM Length L Ch R = 1 ,2088    ,147.2,141.4,136.1
BEGIN DESCRIPTION:
xs 1
END DESCRIPTION:
XS GIS Cut Line= 3
2262551.71169746486708.9244339772262800.00255196486424.000502584
2263067.83104747486283.166673638
#Sta/Elev= 30
       0 2323.42       5  2320.8    28.5  2309.7      37 2304.95    48.3 2297.73
    56.8 2293.14    68.2 2289.59    73.9 2288.82   153.2 2289.37   269.5 2289.26
   360.2 2288.75   459.5 2287.32   512.9 2287.42   527.3 2287.08   531.8 2286.66
   536.3 2285.76   540.8 2283.61   547.3 2282.57   551.9 2282.21   567.9 2282.12
   578.6  2282.2   584.5 2282.61   590.3  2283.5     595 2286.07   596.4 2286.36
   602.3 2287.09   611.2 2288.83   622.2 2290.13   658.6 2292.25   680.5 2293.08
#Mann= 4 ,-1,0
       0      .1       0     110     .05       0   547.3    .045       0
   584.5     .05       0
Bank Sta=547.3,584.5
XS Rating Curve= 0 ,0
Exp/Cntr(USF)=0,0
Exp/Cntr=0.3,0.1

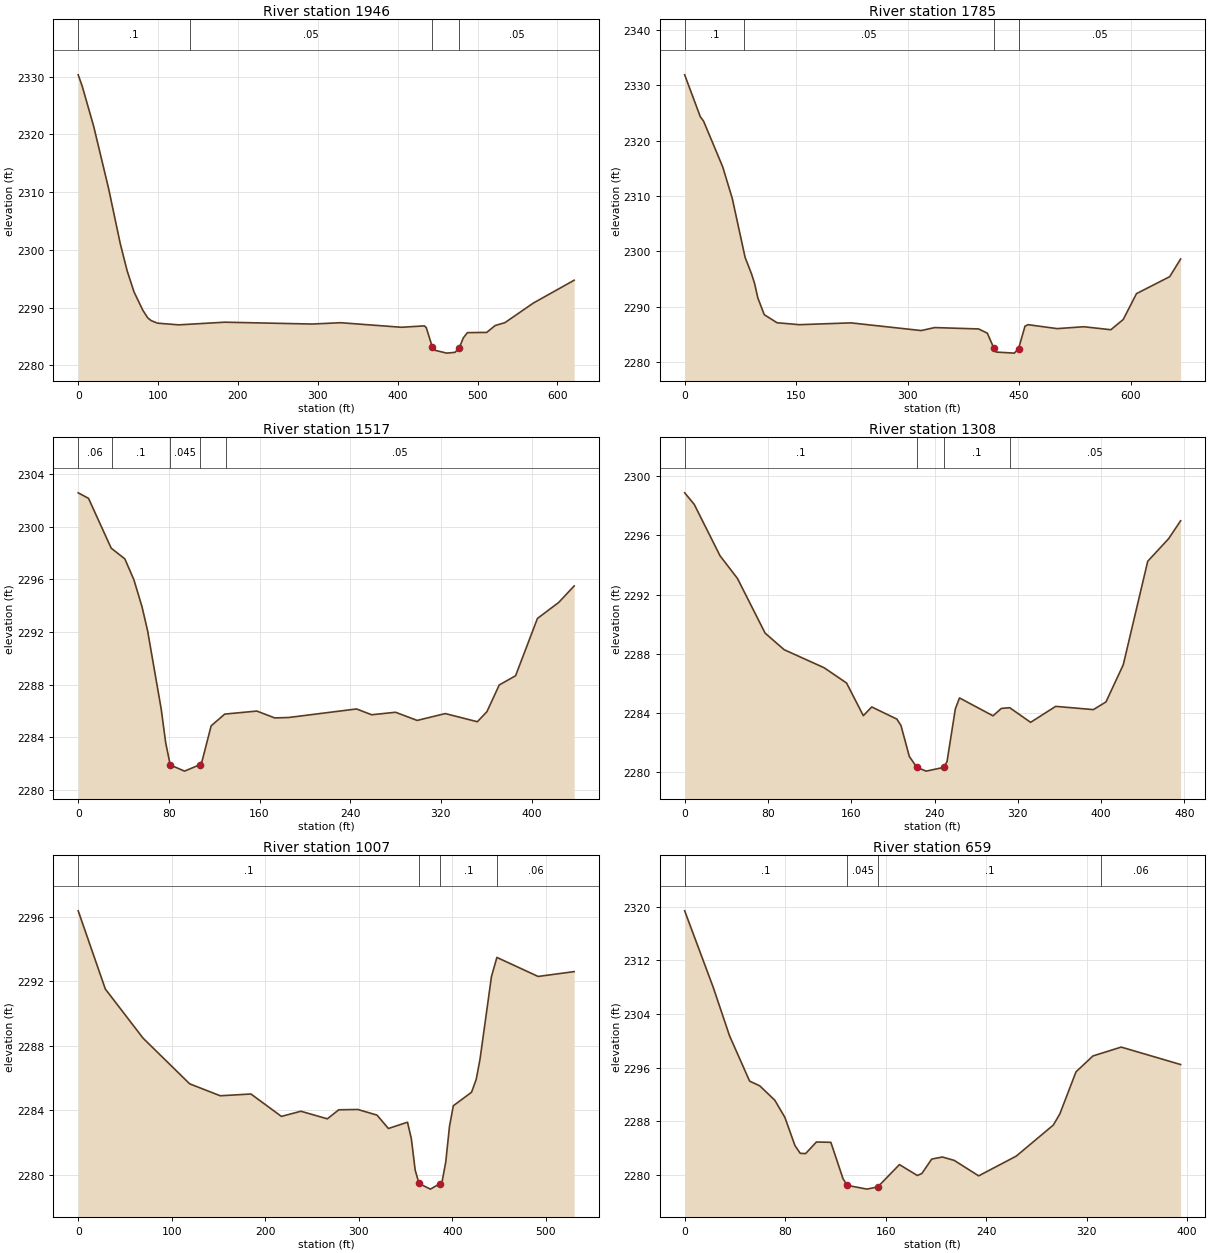
Type RM Length L Ch R = 1 ,1946    ,157.4,160.9,162.6
XS GIS Cut Line= 4
2262835.61292809486849.9932193972262970.59771796486514.653647093
2263121.71276573486391.5543104242263152.27535966486334.673927274
#Sta/Elev= 30
       0 2330.33     5.2 2328.28    19.5 2321.34      38 2310.66    52.6 2301.12
    61.2 2296.41    69.9 2292.71      81 2289.52    87.1 2288.22    91.4 2287.74
    99.4  2287.3   125.9 2287.01   183.6 2287.47   293.1 2287.15   328.6 2287.38
   404.8 2286.59   433.5 2286.83   435.8 2286.53   443.3 2283.23   446.1 2282.62
   461.5 2282.11   471.9 2282.25     477    2283   482.2 2284.74   487.3 2285.66
   511.5  2285.7   522.2  2286.9   534.2 2287.38     570 2290.79     621 2294.74
#Mann= 4 ,-1,0
       0      .1       0     140     .05       0   443.3    .045       0
     477     .05       0
Bank Sta=443.3,477
XS Rating Curve= 0 ,0
Exp/Cntr(USF)=0,0
Exp/Cntr=0.3,0.1

Type RM Length L Ch R = 1 ,1785    ,292.7,267.9,246.1
XS GIS Cut Line= 5
2262913.75808503486884.7867427672263006.25407754  486650.4873979
2263143.78575024486574.0809130712263277.32820193486484.154221084
 2263313.6690641486394.167324294
#Sta/Elev= 30
       0 2331.89    21.1  2324.3    25.4 2323.53    51.2 2315.25    64.1 2309.52
    81.3  2298.9    89.9 2295.93    94.1 2294.17    98.5 2291.55   107.1 2288.54
   124.3 2287.08   154.4 2286.73   223.6 2287.06   318.2 2285.67   336.5 2286.21
   395.5 2285.96   407.2  2285.2   415.9 2282.53   419.3 2281.78   443.5 2281.59
  449.292282.406   457.9 2286.46     462 2286.73   501.3 2286.02     537 2286.36
   573.4 2285.82   590.1 2287.67   607.9 2292.34   652.6 2295.41   667.3  2298.6
#Mann= 4 ,-1,0
       0      .1       0      80     .05       0   415.9    .045       0
  449.29     .05       0
Bank Sta=415.9,449.29
XS Rating Curve= 0 ,0
Exp/Cntr(USF)=0,0
Exp/Cntr=0.3,0.1

Type RM Length L Ch R = 1 ,1517    ,210.6,209.2,209.4
XS GIS Cut Line= 3
2263291.12042438486850.2105341252263272.89807778 486583.88392997
2263368.21496769486442.310314077
#Sta/Elev= 30
       0 2302.57     9.1 2302.15    29.1 2298.37    41.1 2297.56    49.1 2295.98
    56.3 2293.92    61.2 2292.11    73.2 2286.17    77.2 2283.59    81.2 2281.91
    93.8 2281.44  107.082281.917   109.3  2282.2   117.3 2284.88   129.3 2285.77
   157.6    2286   173.4 2285.48   185.5 2285.51   245.6 2286.16   258.9 2285.72
     280 2285.91   299.1 2285.29   323.9 2285.81   352.2 2285.19   360.6 2285.95
   371.5 2287.98   385.9 2288.68   405.2 2293.03     424 2294.25   437.6  2295.5
#Mann= 5 ,-1,0
       0     .06       0      30      .1       0    81.2    .045       0
  107.08      .1       0     130     .05       0
Bank Sta=81.2,107.08
XS Rating Curve= 0 ,0
Exp/Cntr(USF)=0,0
Exp/Cntr=0.3,0.1

Type RM Length L Ch R = 1 ,1308    ,271.7,301.7,334.2
XS GIS Cut Line= 3
2263360.33486501486853.5268196612263493.96670328486780.365590726
 2263463.5318576486457.729222738
#Sta/Elev= 30
       0 2298.88     9.1 2298.11      34 2294.62    50.7 2293.09    77.3 2289.39
    95.6 2288.27     134 2287.05   155.5 2286.02   171.6 2283.81   179.7  2284.4
   203.8 2283.58   207.8 2283.14   215.8 2281.05     223 2280.32   231.9 2280.06
   248.7 2280.31     252  2280.7     260 2284.27     264 2285.01   296.2  2283.8
   304.2  2284.3   312.2 2284.35   332.3 2283.36   356.4 2284.44   392.6 2284.22
   404.7 2284.74   421.3 2287.25   444.8 2294.25   464.9 2295.78   476.4 2296.99
#Mann= 4 ,-1,0
       0      .1       0     223    .045       0   248.7      .1       0
  312.35     .05       0
Bank Sta=223,248.7
XS Rating Curve= 0 ,0
Exp/Cntr(USF)=0,0
Exp/Cntr=0.3,0.1

Type RM Length L Ch R = 1 ,1007    ,355.8,347.5,337.6
XS GIS Cut Line= 3
2263391.83297223486851.5834507262263574.95531453486811.041609713
2263910.68020879486742.278173494
#Sta/Elev= 30
       0 2296.38      29 2291.53    69.4 2288.48   119.2 2285.65   151.9 2284.91
   184.7 2285.02   217.3 2283.63   238.1 2283.95   266.4 2283.48   278.6 2284.04
     299 2284.06   319.5 2283.71   331.7 2282.88   352.1 2283.27   356.2 2282.25
   360.3 2280.31   364.4 2279.47   376.6 2279.12   386.7 2279.46   388.9 2279.52
     393  2280.8     397 2283.01   401.1 2284.29   420.6 2285.13   425.6 2285.93
   429.7  2287.2   441.9 2292.31   447.7 2293.49   491.8 2292.31   530.3 2292.61
#Mann= 4 ,-1,0
       0      .1       0   364.4    .045       0   386.7      .1       0
  447.56     .06       0
Bank Sta=364.4,386.7
XS Rating Curve= 0 ,0
Exp/Cntr(USF)=0,0
Exp/Cntr=0.3,0.1

Type RM Length L Ch R = 1 ,659     ,68.3,45.7,38.6
XS GIS Cut Line= 4
2263572.44542151487117.6585134562263662.85629502487120.041435704
2263729.43794606487073.7847097192263867.72953986486898.402362951
#Sta/Elev= 30
       0 2319.37    22.7 2307.98    35.7 2300.75    51.7 2293.98    59.8 2293.27
    71.8 2291.12    79.8 2288.57    87.8 2284.37      92 2283.21    96.3 2283.17
   104.9  2284.9   116.4 2284.85   126.1 2279.42  129.452278.432   145.2 2277.87
   153.8 2278.21     171 2281.53   185.3  2279.9   188.9 2280.21   196.7 2282.35
   205.2 2282.66   214.7 2282.15   234.1 2279.85     264 2282.79   293.5 2287.42
   298.7 2289.07   311.6 2295.36   325.1 2297.73   347.6 2299.05   394.9 2296.45
#Mann= 4 ,-1,0
       0      .1       0  129.45    .045       0   153.8      .1       0
  331.52     .06       0
Bank Sta=129.45,153.8
XS Rating Curve= 0 ,0
Exp/Cntr(USF)=0,0
Exp/Cntr=0.3,0.1

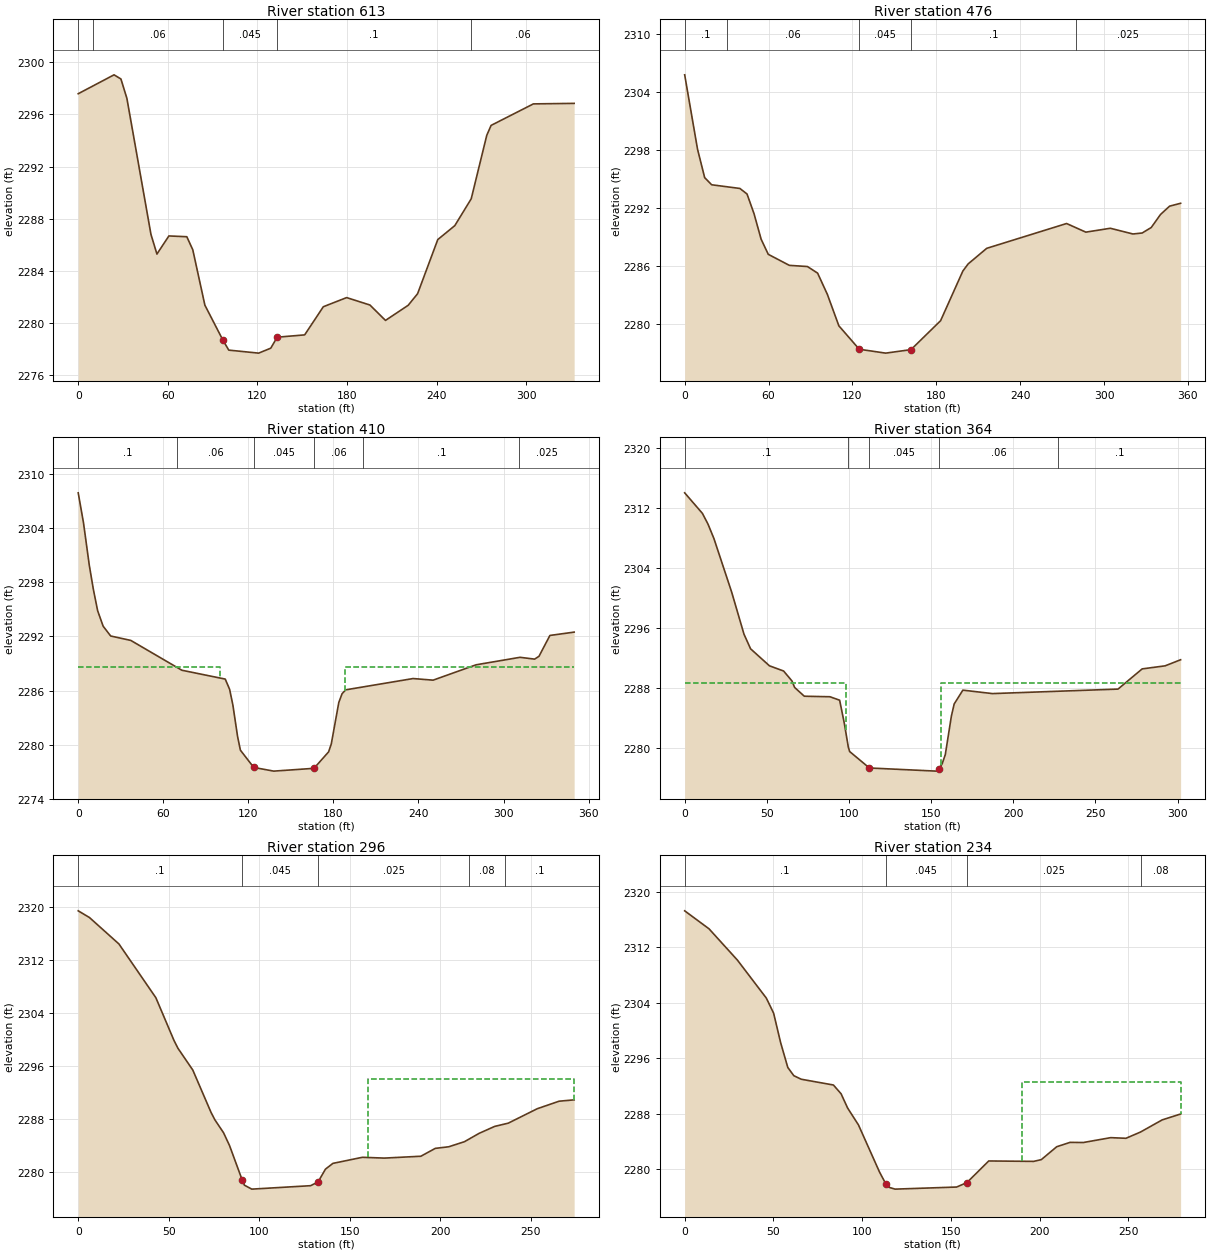
Type RM Length L Ch R = 1 ,613     ,116.9,137.8,137.8
XS GIS Cut Line= 3
2263739.13646764487221.7335257082263748.36115215487088.923274587
2263875.77740645486936.276078837
#Sta/Elev= 30
       0 2297.59      24 2299.04    28.6 2298.72    32.6 2297.23    48.7  2286.8
    52.7 2285.29    60.7 2286.68    72.7 2286.62    76.7 2285.62    84.8 2281.37
    96.8  2278.7   100.8 2277.92   120.8 2277.69   128.9 2278.07   133.1 2278.89
   133.1 2278.91   151.6 2279.09   164.1 2281.25   179.7 2281.95   195.3 2281.38
   205.7  2280.2   220.9 2281.36   227.2 2282.25   240.7  2286.4   252.1 2287.47
   263.1 2289.53   273.5  2294.4   276.4 2295.16   304.7 2296.81     332 2296.85
#Mann= 5 ,-1,0
       0      .1       0      10     .06       0    96.8    .045       0
   133.1      .1       0  263.13     .06       0
Bank Sta=96.8,133.1
XS Rating Curve= 0 ,0
Exp/Cntr(USF)=0,0
Exp/Cntr=0.3,0.1

Type RM Length L Ch R = 1 ,476     ,63.4,65.4,68.1
BEGIN DESCRIPTION:
xs 4
END DESCRIPTION:
XS GIS Cut Line= 2
2263780.36416519487240.4999031482263996.99702845486959.490292789
#Sta/Elev= 30
       0 2305.76     9.2 2298.08    14.3 2295.15    19.3 2294.41    39.5 2294.03
    44.6 2293.46    49.6 2291.43    54.7 2288.79    59.8 2287.23    74.9 2286.09
    87.8 2285.97    95.1 2285.29   102.1 2283.09   110.3 2279.85   124.9 2277.43
   143.8 2277.03   161.9 2277.39   183.1 2280.38     199  2285.5   202.8 2286.24
   216.1 2287.85   273.2 2290.41     287 2289.52   304.5 2289.92   320.7 2289.33
   327.3 2289.43   333.8    2290   340.4 2291.34   346.9  2292.2   354.8  2292.5
#Mann= 5 ,-1,0
       0      .1       0      30     .06       0   124.9    .045       0
   161.9      .1       0     280    .025       0
Bank Sta=124.9,161.9
XS Rating Curve= 0 ,0
Exp/Cntr(USF)=0,0
Exp/Cntr=0.5,0.3

Type RM Length L Ch R = 1 ,410     ,45.7,46.1,46
BEGIN DESCRIPTION:
xs 3
END DESCRIPTION:
XS GIS Cut Line= 4
2263808.97605279487248.6747281762263886.97534164487203.273316254
2263953.79498785487127.6833056822264003.12814722486976.861795975
#Sta/Elev= 30
       0 2307.89     3.7  2304.6     7.8 2299.89    10.7 2297.19    13.7 2294.84
    17.6 2293.12    22.9 2292.04    37.1 2291.55    73.1 2288.25   103.7 2287.27
   106.8 2286.13   109.1 2284.39   112.4 2280.92   114.4  2279.4   123.8 2277.49
   137.9 2277.08   166.3 2277.39   176.6 2279.21   178.5 2280.09   183.8 2284.68
   186.1 2285.65   188.7 2286.08   236.2 2287.33   250.3 2287.15   280.6 2288.85
   311.6 2289.68   321.9 2289.48     325 2289.79   332.7  2292.1   349.8 2292.47
#Mann= 6 ,-1,0
       0      .1       0      70     .06       0   123.8    .045       0
   166.3     .06       0  201.14      .1       0  311.14    .025       0
#XS Ineff= 2 , 0
             100  2288.6     188          2288.6
Permanent Ineff=
       F       F
Bank Sta=123.8,166.3
XS Rating Curve= 0 ,0
Exp/Cntr(USF)=0,0
Exp/Cntr=0.5,0.3

Type RM Length L Ch R = 1 ,364     ,86.9,68.3,53.7
BEGIN DESCRIPTION:
xs 2
END DESCRIPTION:
XS GIS Cut Line= 4
  2263858.525619487279.3167615622263915.50586641487239.775819687
2263994.03289224 487151.740785562264018.93693041487040.054726226
#Sta/Elev= 30
       0    2314    10.8 2311.26    14.2 2309.83    17.8 2307.91    28.6 2300.77
    36.1 2295.16    40.1 2293.22    51.6 2290.95    60.2 2290.26    65.3 2288.93
    66.9 2288.07    72.8  2286.9    88.4 2286.83    94.3 2286.37    97.2 2283.23
    99.6  2280.1   100.4 2279.53   112.4 2277.34   153.2 2276.92   154.5 2277.16
   156.7  2277.9   158.6 2279.12   162.3 2284.25     164 2285.87   169.3 2287.71
   187.3 2287.25   263.7 2287.85   278.4 2290.54   292.4 2290.95   301.8 2291.76
#Mann= 5 ,-1,0
       0      .1       0   99.36     .06       0   112.4    .045       0
   154.5     .06       0  227.32      .1       0
#XS Ineff= 2 , 0
              98  2288.6  156.16          2288.6
Permanent Ineff=
       F       F
Bank Sta=112.4,154.5
XS Rating Curve= 0 ,0
Exp/Cntr(USF)=0,0
Exp/Cntr=0.5,0.3

Type RM Length L Ch R = 1 ,296     ,80.5,61.8,42.4
BEGIN DESCRIPTION:
xs 4
END DESCRIPTION:
XS GIS Cut Line= 3
2264000.24964373487331.286671435 2264031.7602221487168.370276883
2264019.97982554487060.922222826
#Sta/Elev= 30
       0 2319.42     6.2 2318.41    22.5 2314.41    42.9 2306.29    52.9 2299.84
    55.1 2298.65    63.3 2295.36    73.4 2288.95    75.5 2287.84    80.3 2285.88
    83.6 2283.95    90.5 2278.81    91.8 2277.96    95.9 2277.36   128.4 2277.88
   132.5 2278.44   136.6 2280.38   140.7 2281.25     157 2282.17   169.1 2282.05
   189.3 2282.33   197.3 2283.52   204.7 2283.76   213.4 2284.53   221.5 2285.79
   230.1 2286.84   237.6 2287.33   253.6 2289.51   265.7 2290.65     274 2290.85
#Mann= 5 ,-1,0
       0      .1       0    90.5    .045       0   132.5    .025       0
  215.94     .08       0  235.94      .1       0
#XS Ineff= 2 , 0
                          159.84         2293.94
Permanent Ineff=
       F       F
Bank Sta=90.5,132.5
XS Rating Curve= 0 ,0
Exp/Cntr(USF)=0,0
Exp/Cntr=0.5,0.3

Type RM Length L Ch R = 1 ,234     ,53.4,50.2,49.8
BEGIN DESCRIPTION:
xs 3
END DESCRIPTION:
XS GIS Cut Line= 3
2264097.29758998487358.3524952512264109.71310549487293.791814588
2264026.94300208487096.798968461
#Sta/Elev= 30
       0 2317.26    13.7 2314.67    29.7 2310.16      46 2304.68    50.1 2302.51
    54.1 2298.22    58.1 2294.68    61.5 2293.49    65.7 2292.98    83.8 2292.15
    88.1 2290.89    91.8 2288.83    97.9  2286.4   109.8 2279.59   113.2 2277.95
   114.1 2277.48   118.5 2277.14   153.2 2277.44     159 2278.08   171.3  2281.2
   196.6 2281.14   200.9 2281.39   209.6 2283.25   217.1 2283.88   224.6 2283.86
     240 2284.56   248.6 2284.47   256.8 2285.37     269 2287.12   279.4 2287.97
#Mann= 4 ,-1,0
       0      .1       0   113.2    .045       0     159    .025       0
   256.8     .08       0
#XS Ineff= 2 , 0
              70  2292.6     190          2292.6
Permanent Ineff=
       F       F
Bank Sta=113.2,159
XS Rating Curve= 0 ,0
Exp/Cntr(USF)=0,0
Exp/Cntr=0.5,0.3

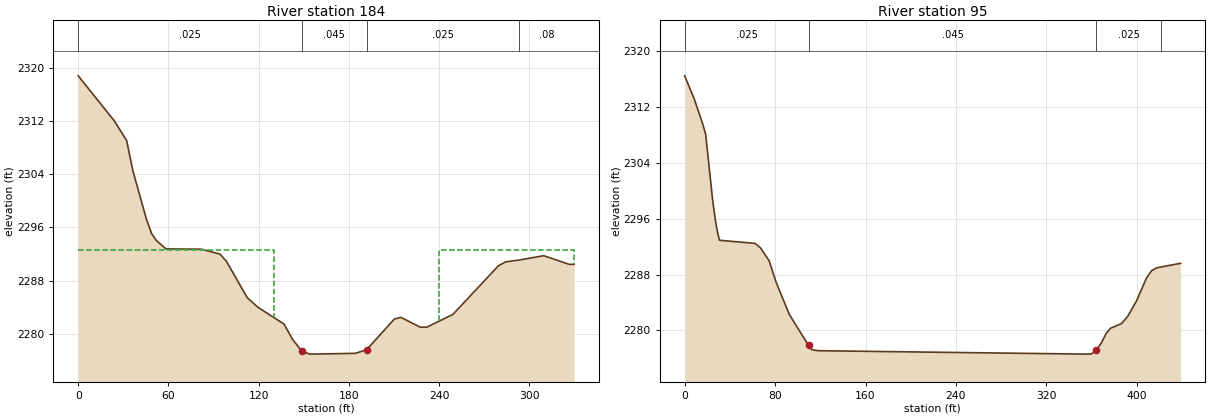
Type RM Length L Ch R = 1 ,184     ,88.9,88.9,88.9
BEGIN DESCRIPTION:
xs 2
END DESCRIPTION:
XS GIS Cut Line= 3
2264123.78402307487392.2882376512264152.95220752487283.702138981
2264070.97669709487082.504571601
#Sta/Elev= 30
       0 2318.78    23.9 2312.04    32.2 2309.05    36.4 2304.45    45.3 2297.27
    48.8 2295.07    51.8 2294.05    58.4 2292.76    81.9 2292.72    94.3 2291.97
    98.5 2290.91   112.4 2285.42   119.5 2283.98   136.8 2281.47   142.6 2279.13
   148.7 2277.37     154 2276.94   184.3 2277.06   191.7  2277.6   210.2 2282.22
   214.5 2282.47   227.5 2280.98   231.8    2281   249.1 2282.91   279.3 2290.21
   284.1 2290.81     293 2291.08   309.5 2291.74   326.5 2290.43   329.7 2290.46
#Mann= 4 ,-1,0
       0    .025       0   148.7    .045       0   191.7    .025       0
     293     .08       0
#XS Ineff= 2 , 0
             130  2292.6     240          2292.6
Permanent Ineff=
       F       F
Bank Sta=148.7,191.7
XS Rating Curve= 0 ,0
Exp/Cntr(USF)=0,0
Exp/Cntr=0.5,0.3

Type RM Length L Ch R = 1 ,95      ,,,
XS GIS Cut Line= 4
 2264140.3711518487407.7165849282264230.04428183487300.057511416
2264206.74449772487120.0987525722264100.81531937487069.815914747
#Sta/Elev= 30
       0 2316.45     8.5 2313.12    15.9 2309.59    18.4 2308.17    18.7 2307.87
    24.7 2298.71    27.2 2295.73    29.3 2293.85    30.9  2292.9    62.2 2292.46
      67 2291.83    74.7 2289.98    80.9  2286.9    92.5 2282.31   109.6 2277.84
   112.4 2277.25   117.8 2277.09   354.6  2276.6   359.8 2276.62   364.3 2277.17
   368.7 2278.22   373.1  2279.6   376.7  2280.3   386.4 2280.97   391.8 2281.95
   399.7  2284.2   408.5 2287.46     413 2288.52   417.4 2288.95   438.8 2289.61
#Mann= 4 ,-1,0
       0    .025       0   109.6    .045       0   364.3    .025       0
  421.57     .08       0
Bank Sta=109.6,364.3
XS Rating Curve= 0 ,0
Exp/Cntr(USF)=0,0
Exp/Cntr=0.3,0.1
LCMann Table=0

Chan Stop Cuts=-1
Use User Specified Reach Order=0
Composite Channel Slope=5